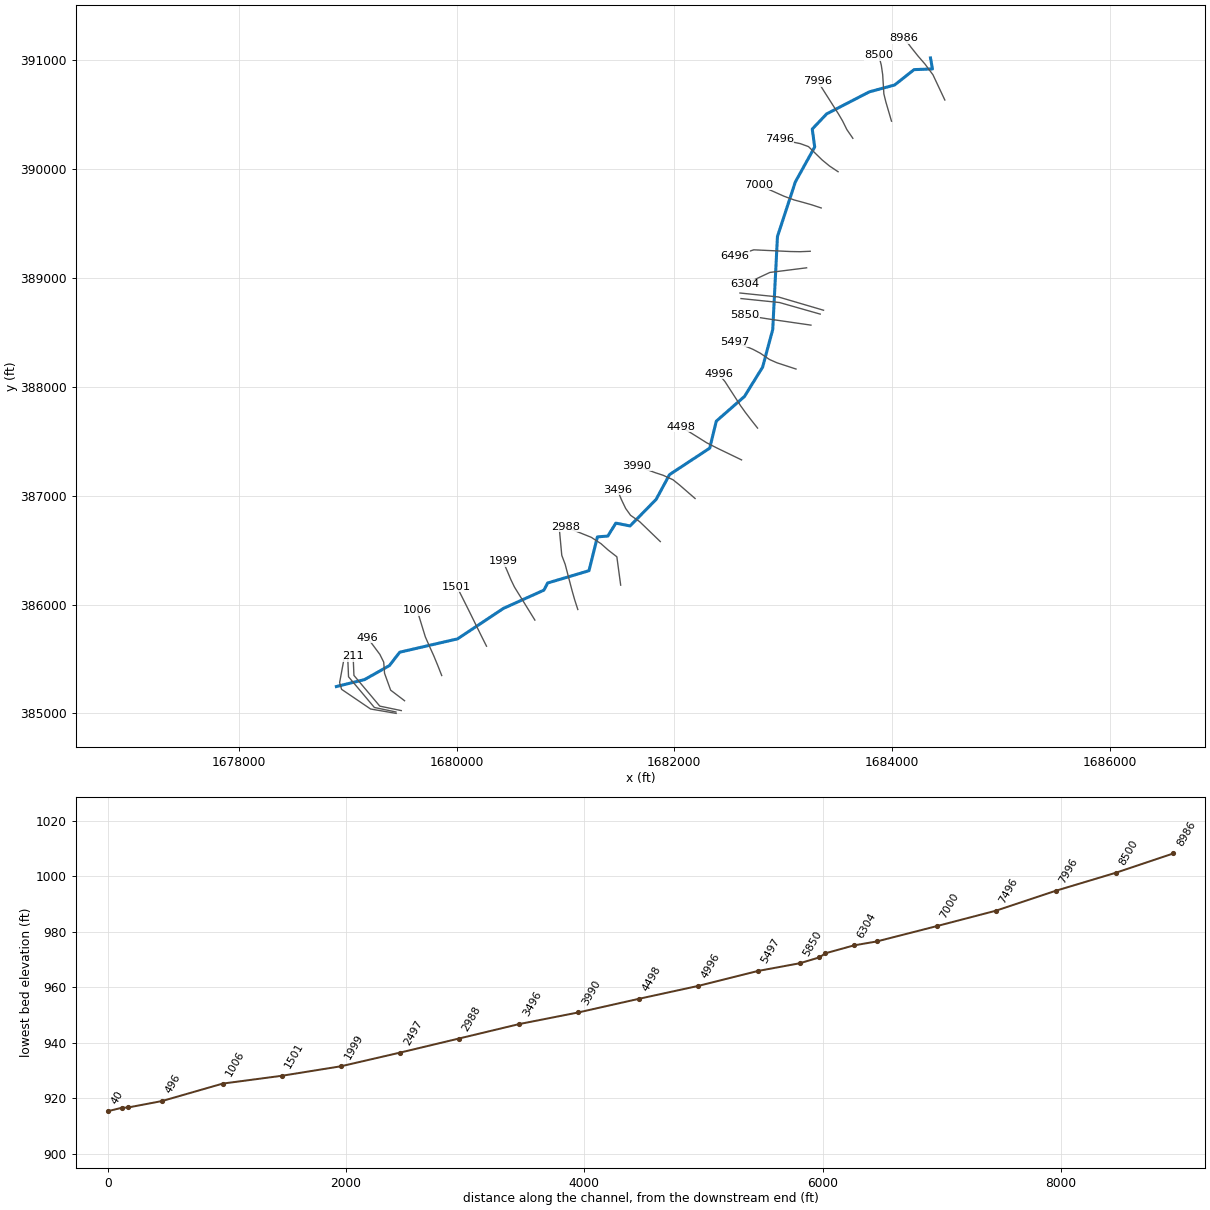
--- WILEYFK.prj (project) ---

Proj Title=WILEYFK
Current Plan=p01
Default Exp/Contr=0,0
English Units
Geom File=g01
Flow File=f01
Plan File=p01
BEGIN DESCRIPTION:
---------- MODELED AS PART OF WVEMD CTP PROGRAM, 2023----------
Stream Name: Wiley Fork
Flood Zone:  AFH
Wetzel County, WV
HEC-RAS Version: RAS 6.3
Vertical Datum: NAVD88
Projection: NAD 1983 StatePlane West Virginia S FIPS 4702 (US Feet)
Terrain: 1-meter West Virginia FEMA R3 South Central (collected 2018-2020)
Land Use: 2019 NLCD
Hydrologic Method:
WV 2010 Regional Regression Equations
Additional Model Notes:
None
END DESCRIPTION:
DSS Export Rating Curves= 0
DSS Export Rating Curve Sorted= 0
DSS Export Volume Flow Curves= 0
DXF OffsetX= 0
DXF OffsetY= 0
DXF ScaleX= 0
DXF ScaleY= 0

--- WILEYFK.p01 (plan) ---

Plan Title=Floodplain
Program Version=4.00
Geom File=g01
Flow File=f01
K Sum by GR=0
Std Step Tol=0.01
Critical Tol=0.01
Num of Std Step Trials=20
Max Error Tol=0.3
Flow Tol Ratio=0.001
Split Flow NTrial=30
Split Flow Tol=0.02
Split Flow Ratio=0.02
Log Output Level=0
Friction Slope Method=1
Unsteady Friction Slope Method=2
Unsteady Bridges Friction Slope Method=1
Global Log Level=0
CheckData=False
Run HTab=0
Run UNet=0
Run PostProcess=0
UNET Theta=0
UNET Theta Warmup=0
UNET ZTol=0
UNET ZSATol=0
UNET MxIter=0
UNET MaxInSteps=0
UNET DtIC=0
UNET DtMin=0
UNET MaxCRTS=0
UNET WFStab=0
UNET SFStab=0
UNET WFX=0
UNET SFX=0
UNET DSS MLevel=0
UNET DZMax Abort=0
UNET Convert EG Bridges=0
UNET Use Existing IB Tables=0
UNET Froude Limit=0
UNET Froude Power=0
Write IC File=0
Echo Input=False
Echo Output=False
Write Detailed=0

--- WILEYFK.f01 (steady flow) ---

Flow Title=Flow
Program Version=6.31
Number of Profiles= 1
Profile Names=F01pct
River Rch & RM=WILEYFK,Main            ,8986
     639
River Rch & RM=WILEYFK,Main            ,7496
     729
River Rch & RM=WILEYFK,Main            ,6496
     815
River Rch & RM=WILEYFK,Main            ,4996
     968
River Rch & RM=WILEYFK,Main            ,2988
    1090
Boundary for River Rch & Prof#=WILEYFK,Main            , 1
Up Type= 0
Dn Type= 3
Dn Slope=0.00758
DSS Import GetInterval= 0
DSS Import GetPeak= 0
DSS Import FillOption= 0

--- WILEYFK.g01 (geometry) ---

Geom Title=Geometry
Program Version=6.31

River Reach=WILEYFK         ,Main
Reach XY= 30
     1684352.657      391021.095     1684370.845      390919.706
     1684202.123      390913.514     1684023.339      390772.267
     1683790.765       390709.19     1683399.142        390506.8
     1683266.795      390367.487      1683289.24      390203.021
      1683111.23      389881.442     1682947.151      389380.305
     1682903.809       388526.63     1682810.934      388181.058
     1682644.146      387911.334     1682385.258      387684.564
     1682325.276      387436.898     1681956.098      387193.875
     1681832.652      386965.945     1681593.499      386722.148
     1681462.701      386748.076     1681389.174      386629.273
     1681293.591      386621.921     1681216.195      386311.177
     1680836.569      386198.179     1680801.741      386132.392
     1680430.241      385964.831     1680009.208      385685.045
       1679477.5      385562.373      1679382.69      385439.314
     1679154.373      385310.837     1678895.926      385247.006

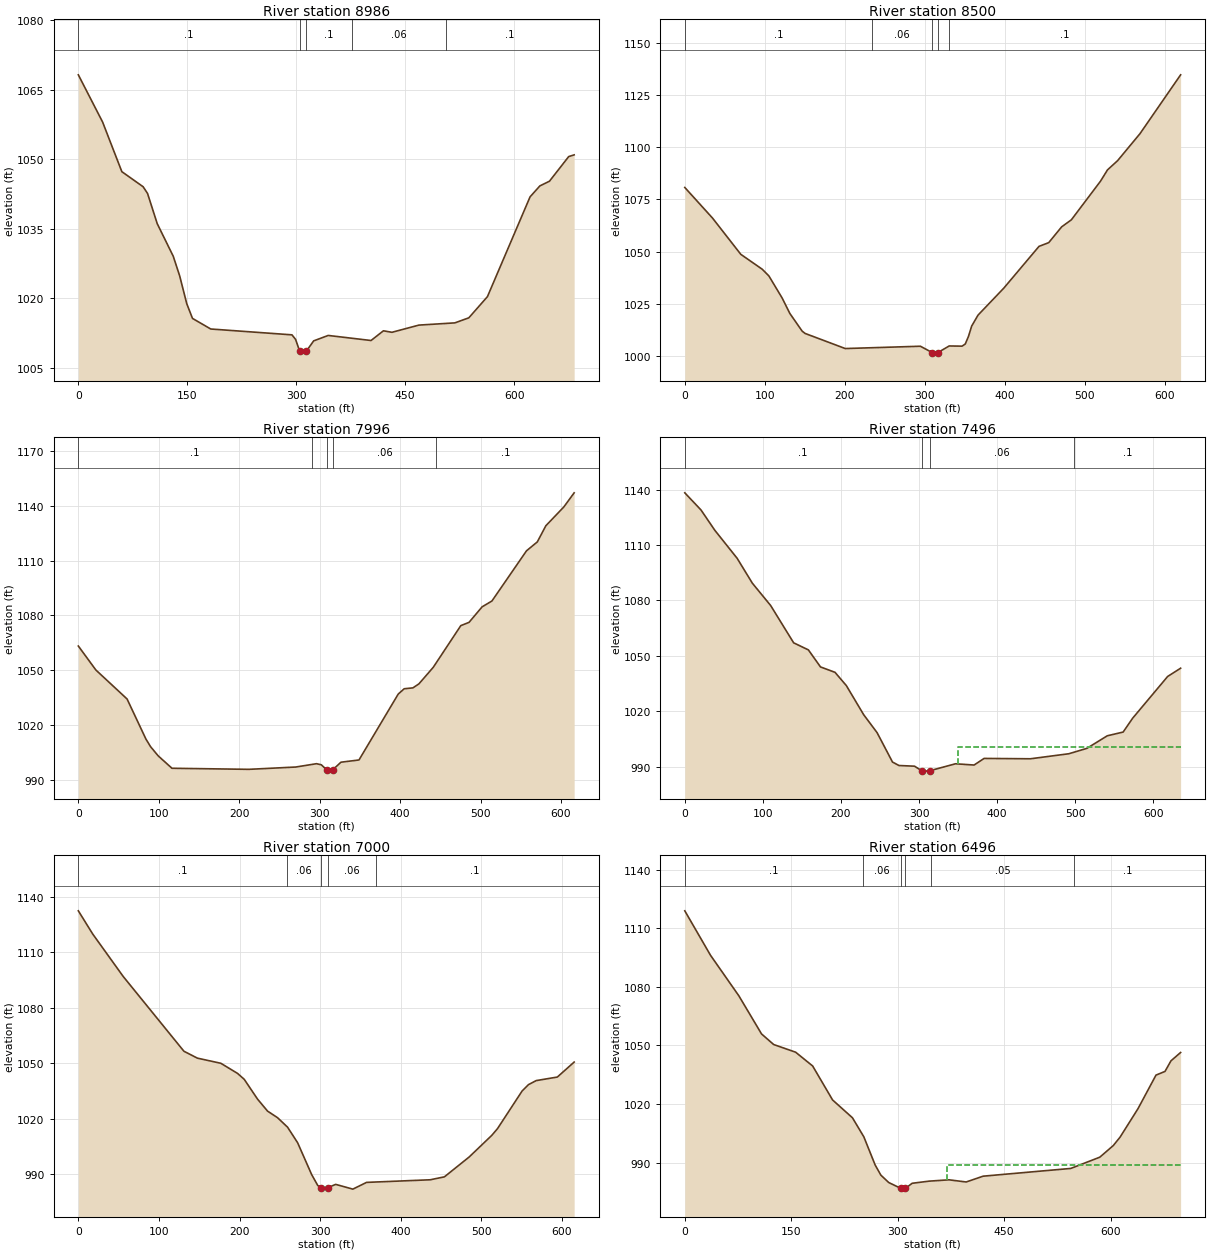
Type RM Length L Ch R = 1 ,8986    ,487.3,486.2,482.7
XS GIS Cut Line= 6
1684484.50721109390634.2958011781684375.39883351390866.156557918
1684302.95278418390963.6012449261684238.35547243 391038.16310367
1684174.08985293391118.5569717591684111.57718268391200.815009341
#Sta/Elev= 30
       0 1068.19    33.4 1058.02    59.9 1047.32    89.2 1044.07    95.3 1042.62
   108.6 1036.12   130.7 1029.08   139.5 1024.87   149.3 1018.85   157.2 1015.69
   182.3 1013.41   294.1 1012.15   299.1 1011.17  304.641008.665   309.1 1008.21
     314 1008.66     324 1010.85     344 1012.02     403 1010.93     420 1013.02
   431.8  1012.7   468.9 1014.25   518.4 1014.73   537.6 1015.82   563.2 1020.38
   621.9 1041.89   635.4 1044.25   648.6 1045.26   675.1 1050.57   682.6 1050.94
#Mann= 5 ,-1,0
       0      .1       0  304.64    .045       0     314      .1       0
  376.25     .06       0  506.33      .1       0
Bank Sta=304.64,314
XS Rating Curve= 0 ,0
Exp/Cntr(USF)=0,0
Exp/Cntr=0.3,0.1

Type RM Length L Ch R = 1 ,8500    ,501.8,503.5,503.8
XS GIS Cut Line= 6
1683994.72275759390439.8460588461683942.97187684390616.212832093
1683924.54540451390690.9220002591683913.75408751390866.671648756
1683901.02675076390953.6504774241683877.55074784391045.711645007
#Sta/Elev= 30
       0 1080.75    34.7 1066.03      70 1048.65    96.8 1041.48   105.1 1038.28
   121.8 1027.59   131.3 1020.26   146.7 1011.76   150.3 1010.67   200.6  1003.4
   294.5 1004.51   309.4 1001.45   314.5  1001.2  316.241001.444   330.5 1004.64
   346.6 1004.55   350.6 1005.59   354.6 1009.22   358.6 1014.19   366.6 1019.47
   398.7 1032.38   442.8 1052.47   454.9 1054.25   471.1 1061.84   483.2 1065.21
   519.6 1083.74   528.4  1089.2     541 1093.61     569 1106.58   619.8 1134.84
#Mann= 5 ,-1,0
       0      .1       0  233.81     .06       0   309.4    .045       0
  316.24     .06       0  330.76      .1       0
Bank Sta=309.4,316.24
XS Rating Curve= 0 ,0
Exp/Cntr(USF)=0,0
Exp/Cntr=0.3,0.1

Type RM Length L Ch R = 1 ,7996    ,501.1,500.8,500.7
XS GIS Cut Line= 6
1683639.71460934390282.5763602551683584.71078233390362.575544089
1683545.64589985390441.430701345 1683507.7470255 390506.21141167
1683366.81620501390727.6722548461683317.67424293390807.522816926
#Sta/Elev= 30
       0 1063.27    21.8 1050.13    60.6 1034.24      84 1012.31    89.8 1008.11
    99.3 1003.07   116.4  996.28   211.9  995.69   270.2  996.95   296.1  998.78
   302.1  998.18  309.03995.3214   311.6  994.71  316.06995.3478   326.5   999.6
   348.9 1000.82   397.7 1036.94   405.1 1039.85   415.9 1040.33   423.4 1042.52
   441.2 1051.58   475.5 1074.45   485.7 1076.23     502 1084.75   514.2 1087.95
   557.2 1115.46   570.6 1120.32   581.2 1129.17   603.5 1139.45   616.4 1147.22
#Mann= 5 ,-1,0
       0      .1       0  290.14     .06       0  309.03    .045       0
  316.06     .06       0  445.14      .1       0
Bank Sta=309.03,316.06
XS Rating Curve= 0 ,0
Exp/Cntr(USF)=0,0
Exp/Cntr=0.3,0.1

Type RM Length L Ch R = 1 ,7496    ,492.5,495.5,497.2
XS GIS Cut Line= 6
1683504.11350259 389975.686226011683425.22225617390028.199572429
1683357.36346801390083.9199334231683232.25741901390206.301250339
1683156.15061584390233.8835442511682963.80355959390273.579987168
#Sta/Elev= 30
       0 1138.31    20.8    1129    38.4 1118.05      67 1102.87    86.5 1089.38
     110 1077.24   139.4 1057.06   158.3 1053.22   173.8 1043.99   192.4 1041.07
   206.9 1033.88   229.1 1018.11   246.3 1008.37     266  992.47   274.3  990.59
   294.2  990.23   303.3  987.79   308.4  987.55     314  987.79   346.7  991.53
   370.5  990.85   383.3  994.43   442.7  994.24   491.9  996.97   514.9  999.88
   541.1 1006.69   561.4 1008.72   573.6 1016.24   618.4 1038.83     635  1043.3
#Mann= 4 ,-1,0
       0      .1       0   303.3    .045       0     314     .06       0
  498.54      .1       0
#XS Ineff= 2 , 0
                          350.25         1000.36
Permanent Ineff=
       F       F
Bank Sta=303.3,314
XS Rating Curve= 0 ,0
Exp/Cntr(USF)=0,0
Exp/Cntr=0.3,0.1

Type RM Length L Ch R = 1 ,7000    ,502.2,503.7,504.5
XS GIS Cut Line= 6
1683348.99832726389642.8361699281683259.39909701389672.426005751
1683174.64696993389696.4574537581683101.40531851389716.099146754
 1683006.8743396389750.7457310111682773.01621151389855.389550582
#Sta/Elev= 30
       0 1132.42    17.9 1119.86    55.7 1096.93     131 1056.53   147.7  1052.8
   176.8 1050.02   197.5 1044.56   205.8 1041.37   222.3 1030.68   234.8 1024.16
   247.2  1020.6   259.6 1015.48   272.1 1007.06   289.5  989.86     297  984.02
  300.63  982.77   309.5  982.79   319.3  984.57   340.6     982   357.6  985.64
   436.6  987.05   454.2  988.64   484.9  999.37   512.9 1011.03     520 1014.65
   550.6 1035.04   558.5 1038.48   568.1 1040.66   594.3 1042.58615.1672 1050.67
#Mann= 5 ,-1,0
       0      .1       0  258.28     .06       0  300.63    .045       0
   309.5     .06       0  368.96      .1       0
Bank Sta=300.63,309.5
XS Rating Curve= 0 ,0
Exp/Cntr(USF)=0,0
Exp/Cntr=0.3,0.1

Type RM Length L Ch R = 1 ,6496    ,191.3,192,192.3
XS GIS Cut Line= 6
1683248.25804317 389245.005600751683154.22378242389241.071881592
1683066.70230393389242.6502905041682991.78349051389246.135191679
1682729.56682333389258.3300491721682559.21509444389201.322982567
#Sta/Elev= 30
       0 1118.94    36.2 1096.21    76.2 1075.43   108.2  1055.9   125.3 1050.49
   156.2 1046.57   180.2 1039.51   208.3 1022.11   236.3 1012.99   252.3 1003.27
   268.3  988.81   276.3  983.65   287.4  979.85   304.5  976.86   308.4  976.47
  310.84976.8177   320.4  979.46   344.4  980.56   372.4  981.23   396.6  980.13
   420.5   983.1     544  987.06   584.9  992.82   603.9  998.78   613.4 1003.05
   638.7 1017.64   664.1 1034.84   676.8 1036.73   685.2 1042.15   698.8 1046.42
#Mann= 6 ,-1,0
       0      .1       0  251.65     .06       0   304.5    .045       0
  310.84     .06       0  346.65     .05       0  549.15      .1       0
#XS Ineff= 2 , 0
                          369.37          988.64
Permanent Ineff=
       F       F
Bank Sta=304.5,310.84
XS Rating Curve= 0 ,0
Exp/Cntr(USF)=0,0
Exp/Cntr=0.3,0.1

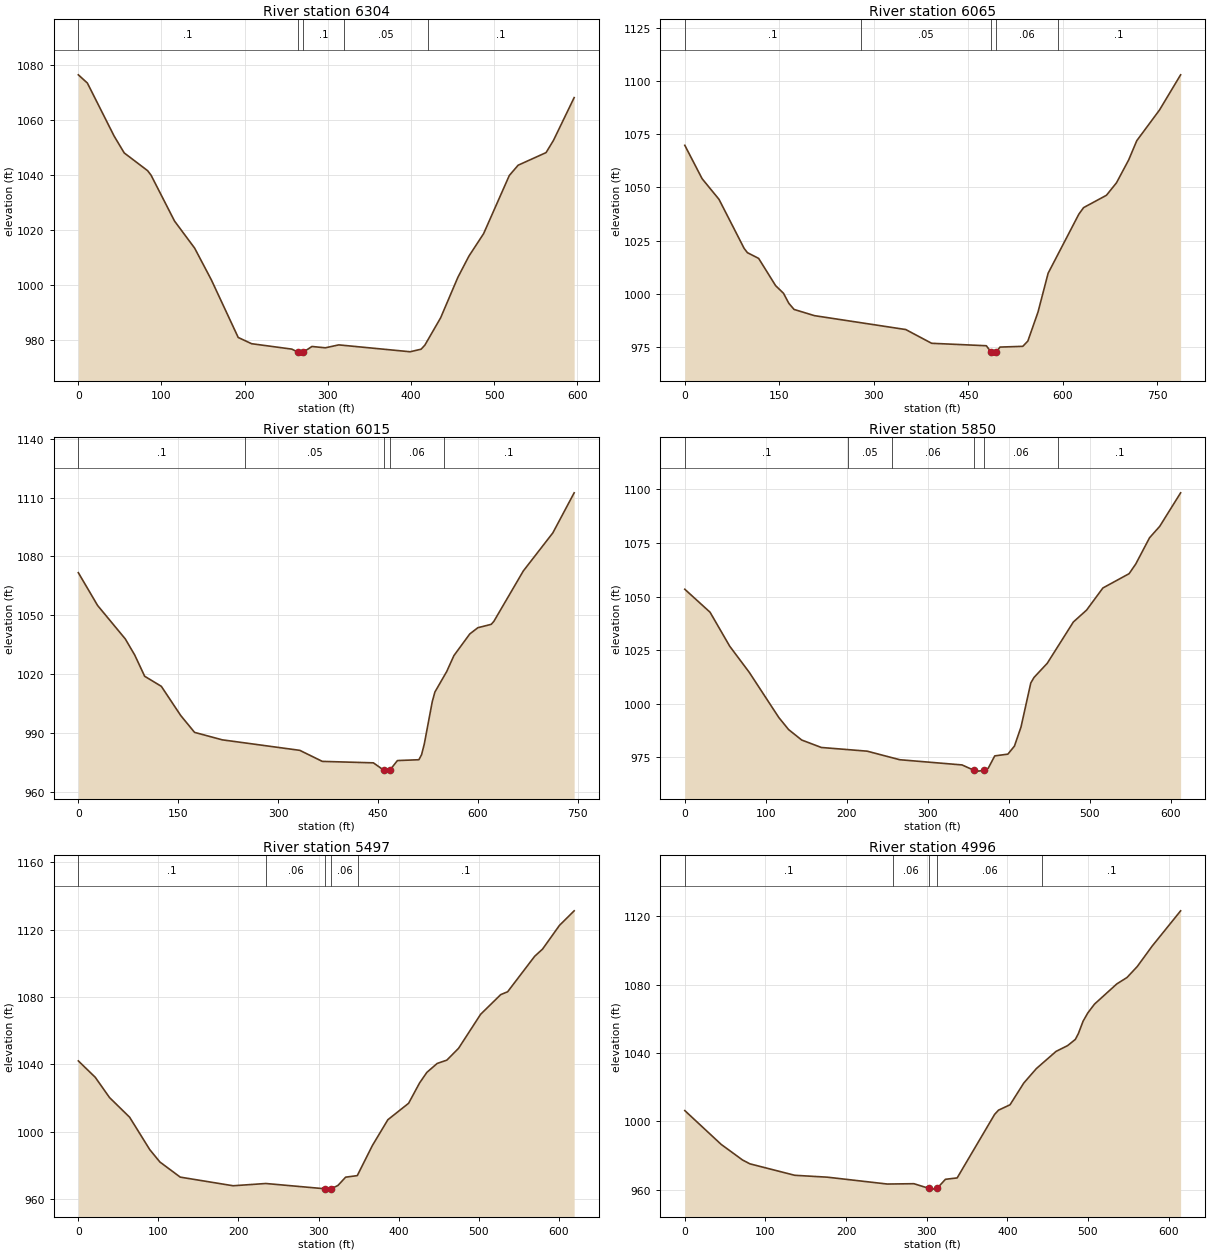
Type RM Length L Ch R = 1 ,6304    ,240.7,239.9,239.4
XS GIS Cut Line= 3
1683214.89913352 389093.13468183 1682877.4060828389050.521922901
1682645.59267422388941.433260042
#Sta/Elev= 30
       0 1076.43    10.9 1073.43    43.1 1054.09    55.2 1047.98    83.4  1041.5
    87.5 1039.86   115.7 1023.17   139.9  1013.3     160 1001.74   192.3  980.76
   208.4  978.48   256.8  976.51  263.91975.4311   268.9  975.05  270.52975.3989
     281  977.47   297.1  976.99   313.3  978.05   399.1  975.55   412.3  976.48
   416.8  977.95   435.8  987.92   456.5 1002.64   469.8 1010.38   487.5 1018.58
   518.4 1039.76     529  1043.5   562.6  1048.1   571.5 1052.54   596.4 1068.13
#Mann= 5 ,-1,0
       0      .1       0  263.91    .045       0  270.52      .1       0
     320     .05       0  420.17      .1       0
Bank Sta=263.91,270.52
XS Rating Curve= 0 ,0
Exp/Cntr(USF)=0,0
Exp/Cntr=0.3,0.1

Type RM Length L Ch R = 1 ,6065    ,49.8,49.9,49.8
XS GIS Cut Line= 3
1683370.47795915388703.4826269621682956.21385028388825.314927323
1682602.89361163 388861.68612836
#Sta/Elev= 30
       0 1069.82    27.5 1054.12    54.3 1044.43    94.2 1021.38    99.4 1019.38
   117.2 1016.69   144.2 1003.88   156.7 1000.29   165.1   995.6   173.4  992.72
   205.7   989.8   350.7  983.27   391.8  976.81   478.6  975.66   485.9  972.78
   488.2  972.19  494.41972.7723   500.3  975.03   536.5  975.38   544.5  977.85
   560.6  991.44   576.7 1009.73   625.5 1037.49     633 1040.54   669.2 1046.33
   685.2  1052.2   704.6 1062.98   717.4 1071.98   753.6 1086.45     787 1102.92
#Mann= 5 ,-1,0
       0      .1       0     280     .05       0   485.9    .045       0
  494.41     .06       0  591.81      .1       0
Bank Sta=485.9,494.41
XS Rating Curve= 0 ,0
Exp/Cntr(USF)=0,0
Exp/Cntr=0.3,0.1

Type RM Length L Ch R = 1 ,6015    ,165.3,164.4,164.3
XS GIS Cut Line= 3
1683339.93228143388667.8401489171682965.55371491388774.331856063
1682612.23347626  388810.7030571
#Sta/Elev= 30
       0 1071.75    28.9 1055.08    70.5 1038.03    84.6 1029.88    99.6 1019.03
   124.6  1013.9   153.7  999.06   174.5  990.46   216.1  986.66   332.5  981.31
   366.3  975.69     443  974.95     459   971.1   463.1  970.73  467.37971.1064
   479.1  976.11   511.3  976.53   515.3  979.09   519.4  984.54   531.4 1006.15
   535.4 1011.05     553 1021.39   563.9 1029.55   587.7 1040.57   599.8 1043.74
   619.9 1045.46   623.9 1047.01   668.1 1072.65   712.4 1092.02   744.4 1112.41
#Mann= 5 ,-1,0
       0      .1       0     250     .05       0     459    .045       0
  467.37     .06       0  549.23      .1       0
Bank Sta=459,467.37
XS Rating Curve= 0 ,0
Exp/Cntr(USF)=0,0
Exp/Cntr=0.3,0.1

Type RM Length L Ch R = 1 ,5850    ,354.2,353.5,350.8
XS GIS Cut Line= 6
1683255.03529385388566.5915351481683162.25496761388580.040327144
1682902.46939794388617.6924828111682828.30944127388628.895872486
1682741.90311802388642.7508316461682649.37410361388657.931575564
#Sta/Elev= 30
       0 1053.44    31.2 1042.73    55.5 1026.87    79.7 1014.65   116.1  993.64
   128.2     988   144.4  983.12   168.7  979.64   225.3  977.92   265.5  973.93
   342.5   971.5  357.51968.9415   362.7  968.61  369.08968.9559   374.8  969.94
   382.9  975.72   399.1  976.53   407.2  980.28   415.3  989.15   427.4 1009.72
   431.4 1012.31   447.7 1018.89     480 1038.18   496.3 1043.71   516.5 1054.04
   548.9 1060.72   557.1 1065.24   574.1 1077.45   586.7  1082.8   612.5 1098.42
#Mann= 6 ,-1,0
       0      .1       0  201.25     .05       0  256.25     .06       0
  357.51    .045       0  369.08     .06       0  461.25      .1       0
Bank Sta=357.51,369.08
XS Rating Curve= 0 ,0
Exp/Cntr(USF)=0,0
Exp/Cntr=0.3,0.1

Type RM Length L Ch R = 1 ,5497    ,502.1,500.3,497.9
XS GIS Cut Line= 6
1683117.38199259  388163.44378751682942.69008476388220.738948509
1682873.34376676388251.3520762621682790.39380142388308.143301249
1682723.56388259388343.707862675 1682554.6449291388414.769400343
#Sta/Elev= 30
       0    1042    21.1 1032.28      39  1020.2    64.1 1008.52    89.2  989.29
   101.9  981.92   127.3  972.94   193.3  967.81   234.2  969.15  308.66965.9895
   311.3  965.81   315.5965.9863   324.2  967.97   333.9  972.92   348.4  973.83
   367.3  991.74   386.6 1007.04   412.5 1016.81   426.2 1028.88   435.3 1035.17
   448.2 1040.48   460.3 1042.46   474.9 1049.47   502.5 1069.71   527.6 1081.39
   536.2 1083.08     570 1104.17   579.8 1108.42   600.9 1122.49   619.3 1131.17
#Mann= 5 ,-1,0
       0      .1       0  233.88     .06       0  308.66    .045       0
   315.5     .06       0  349.68      .1       0
Bank Sta=308.66,315.5
XS Rating Curve= 0 ,0
Exp/Cntr(USF)=0,0
Exp/Cntr=0.3,0.1

Type RM Length L Ch R = 1 ,4996    ,495.4,498.8,500.7
XS GIS Cut Line= 6
1682764.50638601387621.1253183341682705.95499392387695.175695166
1682652.28515376387765.2480615821682608.28950684387826.825038165
1682465.61853234388047.1684295091682406.09240468388120.123664171
#Sta/Elev= 30
       0 1006.38    45.1  986.61    71.6  977.48    80.8  975.22   136.4  968.52
   176.6  967.43   251.1  963.41   284.2   963.6   303.3   960.8   308.1  960.43
   312.8  960.81   323.3  966.18   337.8  966.98   384.3 1004.16   389.1 1006.62
   403.4 1009.77   420.5 1022.52   436.1 1030.96   460.5    1041   474.8 1044.37
   484.4 1048.01   488.2 1051.44     494 1058.64   499.8 1063.45   508.2 1068.67
   535.9  1080.5   548.5 1084.23   561.2 1090.64   579.7  1102.6     615 1123.23
#Mann= 5 ,-1,0
       0      .1       0  258.35     .06       0   303.3    .045       0
   312.8     .06       0  443.35      .1       0
Bank Sta=303.3,312.8
XS Rating Curve= 0 ,0
Exp/Cntr(USF)=0,0
Exp/Cntr=0.3,0.1

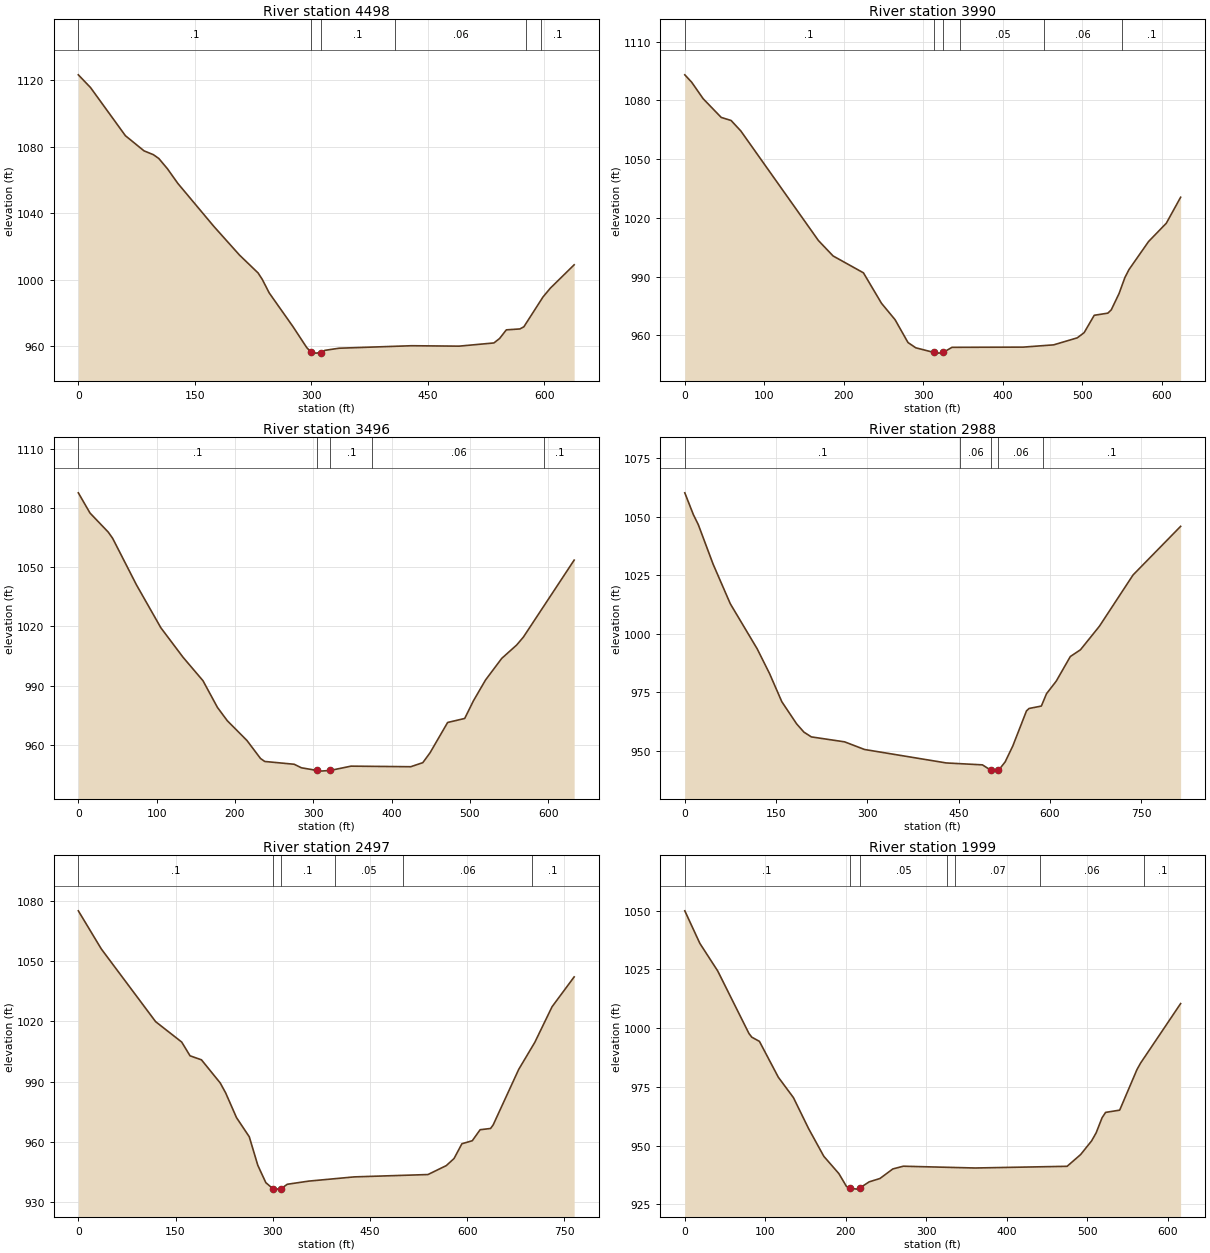
Type RM Length L Ch R = 1 ,4498    ,507.8,507.4,508.4
XS GIS Cut Line= 6
1682617.39316317387328.8332520131682386.62590818387440.236244425
1682295.97090575387486.7345110031682226.76631975387530.444397345
1682145.31175825387581.0594535921682057.79224826387634.080016837
#Sta/Elev= 30
       0  1123.3    15.7 1115.63    60.6 1086.65    84.6 1077.52    96.6 1075.23
   103.6 1072.93   114.6 1066.81   128.1 1057.93   174.5 1032.02   207.4 1014.82
   231.4 1004.02   236.8 1000.12   245.7     992   276.2  971.78     294   959.1
   299.9  956.18   305.9  955.77   311.8  956.14   317.5  957.45   335.5  958.72
   428.9  960.22   490.2  959.97   534.9   961.9   542.2  964.56   550.9  969.78
   568.4  970.33   573.5  971.64   598.1  989.58   607.4   994.8   638.2 1008.94
#Mann= 6 ,-1,0
       0      .1       0   299.9    .045       0   311.8      .1       0
  408.13     .06       0  575.89     .05       0  595.89      .1       0
Bank Sta=299.9,311.8
XS Rating Curve= 0 ,0
Exp/Cntr(USF)=0,0
Exp/Cntr=0.3,0.1

Type RM Length L Ch R = 1 ,3990    ,494.3,494.5,492.3
XS GIS Cut Line= 6
1682190.57216643386974.3539740891682047.89003709387098.248739421
1681987.29271734387146.7591410881681895.80799218387188.033336759
1681824.54927643387211.4581586721681654.55683425387274.971155003
#Sta/Elev= 30
       0 1093.03     8.6 1089.28    23.1 1080.82    45.8 1071.27    58.2 1069.71
    70.4 1064.38     168 1008.39   186.4 1000.52   224.6  991.89   247.3  976.33
   264.4  967.94   280.6  956.29   290.4  953.59   312.7  951.27   318.7  950.87
   325.1951.2636   335.9  953.83   425.6  953.94   463.7  955.09   493.5  958.68
   502.1  961.34   514.8   970.2   531.9  971.29   536.2  972.99     546  981.31
   553.3  989.44   558.4   993.5   583.1 1007.88   605.4 1017.22   623.4 1030.49
#Mann= 6 ,-1,0
       0      .1       0   312.7    .045       0   325.1      .1       0
  346.59     .05       0  451.96     .06       0  549.57      .1       0
Bank Sta=312.7,325.1
XS Rating Curve= 0 ,0
Exp/Cntr(USF)=0,0
Exp/Cntr=0.3,0.1

Type RM Length L Ch R = 1 ,3496    ,508.6,507.7,506.2
XS GIS Cut Line= 6
1681871.25193892386578.5791750851681680.68604709386762.254988834
  1681597.973286386820.0488364991681552.77127667386883.232437178
1681513.03316717386966.2181635951681475.98435676387056.917785332
#Sta/Elev= 30
       0 1087.57    14.9 1077.35    38.2 1067.69    43.8 1064.56    74.3 1040.94
   105.4 1019.27   133.7 1004.35   159.2  992.46   177.7  978.93   190.3  972.19
   215.3  962.23   232.7  953.09   238.1  951.58   275.7  950.17   284.9  948.38
   304.4  947.06   309.3  946.69   321.9 947.046   348.3  949.21   424.6  948.92
     440  950.98   449.2  955.96   471.7  971.32   493.5  973.35   504.7  982.32
   520.1  992.82   540.8 1003.76   559.8  1010.5   568.5 1014.57   633.3 1053.51
#Mann= 5 ,-1,0
       0      .1       0   304.4    .045       0   321.9      .1       0
  375.59     .06       0  595.29      .1       0
Bank Sta=304.4,321.9
XS Rating Curve= 0 ,0
Exp/Cntr(USF)=0,0
Exp/Cntr=0.3,0.1

Type RM Length L Ch R = 1 ,2988    ,494.7,491.5,484.9
XS GIS Cut Line= 6
 1681507.2226864386178.5291611361681472.05752733386438.763837919
1681392.66792235386500.4303812531681326.02829184 386559.61234951
1681237.41167118386617.6332308351680999.52172701386713.207842842
#Sta/Elev= 30
       0  1060.1    14.1 1050.79    22.2 1046.54    46.4 1029.76    74.7 1012.84
   119.1  993.51   139.3  983.02   159.4  971.05   183.7  961.61   195.8  958.07
   207.9  956.05   262.6  953.94   295.2  950.69   429.5  944.95     489  944.13
   503.4  941.76   511.1  941.46  515.34 941.762   526.3  945.39   538.8  952.13
   561.4  967.15   565.6  968.17   585.8   969.2   594.3  974.48   610.2   979.8
   633.4  990.32   650.1  993.21   681.3 1003.27   736.4 1025.07   814.6 1045.81
#Mann= 5 ,-1,0
       0      .1       0  452.25     .06       0   503.4    .045       0
  515.34     .06       0  588.17      .1       0
Bank Sta=503.4,515.34
XS Rating Curve= 0 ,0
Exp/Cntr(USF)=0,0
Exp/Cntr=0.3,0.1

Type RM Length L Ch R = 1 ,2497    ,494.5,497.5,498.1
XS GIS Cut Line= 6
1681113.42438634385954.6965645851681084.67214726386044.101569504
1681060.67875692386128.2775822581680997.26188901386370.103214085
1680966.16516642386452.252328008 1680943.5181164 386697.03912458
#Sta/Elev= 30
       0 1075.17    35.5 1056.14   119.3  1019.9   159.5 1009.74   172.4 1002.88
     190 1000.88     219  989.33   227.3  984.41   244.1  972.05   263.8   962.5
   276.9  948.33   289.3  939.65  300.17936.6365   309.7  936.41     313  936.64
   322.4  938.83   355.4   940.4   425.7  942.51   539.5  943.68   567.8  948.14
   579.8  951.69   591.9  959.04   607.9  960.54     620  966.03   636.1  966.65
   640.1  968.41   679.5  996.08   704.4 1009.61     731 1027.34   765.1 1042.23
#Mann= 6 ,-1,0
       0      .1       0  300.17    .045       0     313      .1       0
  396.45     .05       0  501.45     .06       0  699.29      .1       0
Bank Sta=300.17,313
XS Rating Curve= 0 ,0
Exp/Cntr(USF)=0,0
Exp/Cntr=0.3,0.1

Type RM Length L Ch R = 1 ,1999    ,498.5,497.9,497.1
XS GIS Cut Line= 6
1680718.99657982385857.7216134791680584.25209864386075.685088304
1680531.66788623386160.7433171391680498.84675764386228.586029228
1680464.47543531386310.3978734731680426.19139115386397.937396553
#Sta/Elev= 30
       0 1049.89    18.7 1036.05    40.9  1024.3    79.7  997.69    83.3  996.11
    92.7  994.35   116.2  979.07   134.9  970.43   153.8  957.21   172.7  945.43
   191.4  938.07   200.8  932.63   204.7  931.97   213.4  931.47  217.43931.9565
     229  934.56   242.4  935.99   258.4  940.05   271.4  941.22   360.5  940.46
   474.9  941.18   491.7  946.18   505.3  951.99     511  955.44   518.3  961.82
   522.7  964.12   540.2  965.08   561.7  982.37   566.3  985.17   615.9 1010.42
#Mann= 7 ,-1,0
       0      .1       0   204.7    .045       0  217.43     .05       0
  326.25     .08       0  336.25     .07       0  441.62     .06       0
  570.35      .1       0
Bank Sta=204.7,217.43
XS Rating Curve= 0 ,0
Exp/Cntr(USF)=0,0
Exp/Cntr=0.3,0.1

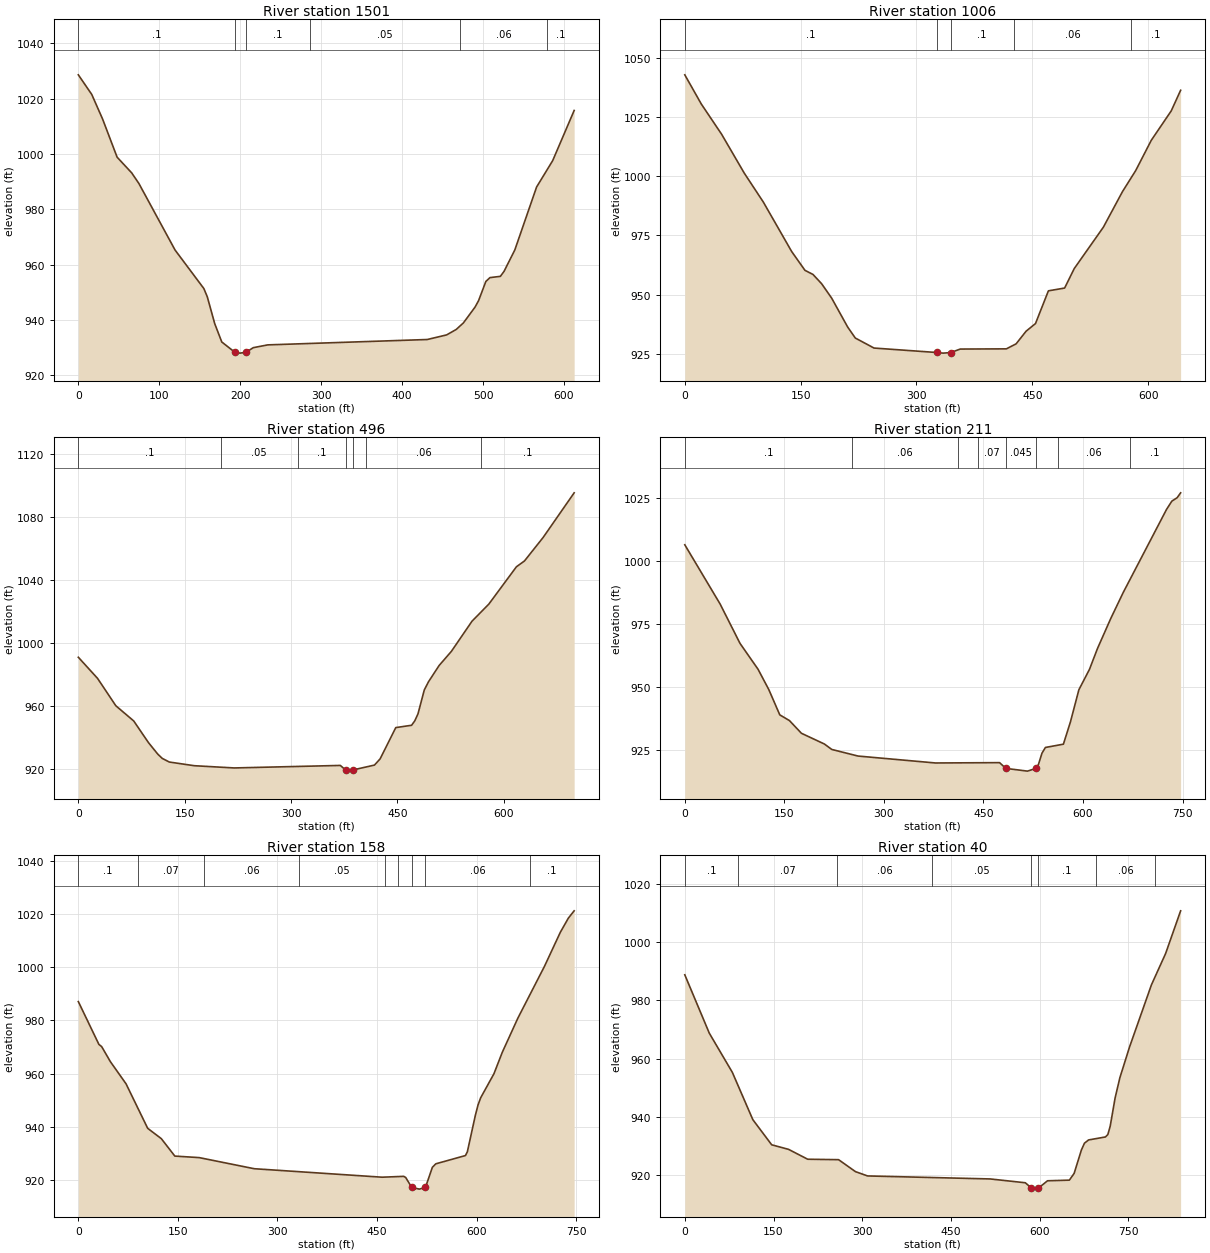
Type RM Length L Ch R = 1 ,1501    ,494.3,495.2,494.3
XS GIS Cut Line= 6
1680274.94972506385617.7152824271680232.79331331385701.451991604
1680161.02081907385847.2427105181680116.77746923385936.922977345
1680044.12571165386082.2809543481680001.90269898386165.989448355
#Sta/Elev= 30
       0 1028.64    16.6 1021.54      30 1012.64    47.9  998.87    65.9   993.2
    74.8  989.36   119.5   965.3   155.1  951.36   159.3   948.4   168.5  938.68
   177.2  932.06  193.42928.3283   199.7  928.03   207.1  928.33   216.1     930
     234  931.01     431  932.95   454.9  934.61   466.8  936.58   475.7  938.96
     490  944.64   494.4  946.98   503.4  953.93   508.5  955.33   521.3  955.78
   525.8  957.54   539.2  965.33   566.1  988.08     586  997.63   612.5 1015.75
#Mann= 6 ,-1,0
       0      .1       0  193.42    .045       0   207.1      .1       0
  286.25     .05       0  471.25     .06       0  578.75      .1       0
Bank Sta=193.42,207.1
XS Rating Curve= 0 ,0
Exp/Cntr(USF)=0,0
Exp/Cntr=0.3,0.1

Type RM Length L Ch R = 1 ,1006    ,508.2,510.2,503
XS GIS Cut Line= 6
1679863.42983909385348.0842607621679827.33870393385440.210388839
1679790.96508901385528.294202179  1679755.713191385606.362615585
1679713.01347326 385703.196739511679637.65470009385948.115212917
#Sta/Elev= 30
       0 1042.99    21.4 1030.62    47.7 1017.83      77 1001.39   101.7  989.14
   138.4  968.21   155.6  960.25     166  958.51   177.2  954.58   190.2  948.47
   210.9  936.26   220.8   931.6     245  927.37     326  925.49   334.7  925.22
  344.39925.4672   356.6  926.94   416.4  927.03     429  929.15   441.9  934.49
   454.1  937.74   470.8  951.58   491.8  952.76   504.3  961.02     542  978.53
   566.7  993.56   583.8 1002.45     604 1015.28   629.9 1027.76     642 1036.45
#Mann= 5 ,-1,0
       0      .1       0     326    .045       0  344.39      .1       0
  425.73     .06       0  578.23      .1       0
Bank Sta=326,344.39
XS Rating Curve= 0 ,0
Exp/Cntr(USF)=0,0
Exp/Cntr=0.3,0.1

Type RM Length L Ch R = 1 ,496     ,267.8,284.9,295.8
XS GIS Cut Line= 6
1679522.24552036385116.7081094791679394.46883476385213.919502839
1679338.22583701385369.2991133331679330.80492009385471.187361002
1679295.17408584385542.6635960041679181.06539017385695.786321253
#Sta/Elev= 30
       0  991.18    27.1  977.78    52.9  960.39    78.1  950.76    98.8  937.07
     112  929.71   118.4  926.97   128.3  924.69   163.4  922.36   219.8  920.94
   369.4  922.53  376.76919.6732   381.4  918.92   387.1  919.66   417.5  922.75
   425.5  926.69   447.6  946.54   469.9  948.02   474.4  950.84   478.9  955.26
   487.8  970.44   493.8  975.67   508.7  985.94     526  994.92   555.1 1014.07
   578.8 1024.91   617.7 1048.59   629.1 1052.31   655.4 1067.22   699.1 1095.52
#Mann= 7 ,-1,0
       0      .1       0  200.55     .05       0  309.77      .1       0
  376.76    .045       0   387.1      .1       0  406.04     .06       0
  568.06      .1       0
Bank Sta=376.76,387.1
XS Rating Curve= 0 ,0
Exp/Cntr(USF)=0,0
Exp/Cntr=0.3,0.1

Type RM Length L Ch R = 1 ,211     ,63.2,52.4,48.9
XS GIS Cut Line= 4
1679492.18576222385026.2027739991679294.61426221385067.208179661
1679057.27994459385349.2756670971679049.82441629385525.723170251
#Sta/Elev= 30
       0 1006.54    53.2  983.01    83.2  967.36   110.4  957.07   126.7  948.93
   143.1  938.96   157.7  936.68   175.7  931.64   210.2  927.39   221.5  925.21
     261  922.59   377.7  919.84   474.2  919.97  483.75 917.685   516.3   916.6
  529.35917.7202   532.9  919.33   538.1  923.72   543.3     926   570.4  927.31
     581  936.16   593.7  948.92   609.7  957.06   621.7   965.3   641.7  977.22
   660.4  987.52   725.8 1020.61   733.8 1023.89   741.8 1025.26     747 1027.19
#Mann= 8 ,-1,0
       0      .1       0  251.78     .06       0  411.78     .05       0
  441.78     .07       0  483.75    .045       0  529.35     .07       0
  561.78     .06       0  670.41      .1       0
Bank Sta=483.75,529.35
XS Rating Curve= 0 ,0
Exp/Cntr(USF)=0,0
Exp/Cntr=0.3,0.1

Type RM Length L Ch R = 1 ,158     ,121.6,117.9,113.4
XS GIS Cut Line= 4
1679442.48224021385013.776893495 1679244.9107402385054.782299158
1679007.57642258385336.8497865931679000.12089427385513.297289747
#Sta/Elev= 30
       0  987.12      31  970.99    35.1  970.19    48.3   964.5    71.9  956.15
   104.5   939.4     125  935.52   145.4  928.95   182.2  928.37   265.1  924.19
   457.7     921   490.3  921.32   493.2  920.89   502.2917.1868   513.7  916.51
     523  917.17   533.4  924.73   538.6  926.04   583.2  929.15   586.1  930.56
   598.1  944.24   602.1  948.13   606.1  950.87   626.2  959.97   638.7  968.01
   662.2  980.89   702.2 1000.35   726.2 1013.23   738.3 1018.55     747 1021.29
#Mann= 9 ,-1,0
       0      .1       0      90     .07       0     190     .06       0
  331.78     .05       0  461.78     .07       0  481.78     .06       0
   502.2    .045       0     523     .06       0  680.41      .1       0
Bank Sta=502.2,523
XS Rating Curve= 0 ,0
Exp/Cntr(USF)=0,0
Exp/Cntr=0.3,0.1

Type RM Length L Ch R = 1 ,40      ,,,
XS GIS Cut Line= 5
1679444.96741631385000.6606862971679210.25634013385040.699634587
1678943.79023599385221.5652285861678925.84174193385283.694631105
1678964.50003683 385493.55394628
#Sta/Elev= 30
       0  988.75    41.4  968.74    80.4  955.29     115  939.08   146.9  930.45
   175.4  928.89   207.8   925.5     260  925.35   288.5  921.25     309  919.77
   516.3  918.74   575.7  917.43  586.08915.6125   588.2  915.25  597.78915.6022
   613.2  918.11   650.1  918.33   658.2  920.65   670.4  928.64   675.6     931
   682.6  932.12   711.1  933.14   715.2  933.98   719.2  936.88   727.4  946.47
   735.5  953.45   751.8  963.97   788.9  985.33   812.8  996.03   838.2 1010.69
#Mann= 8 ,-1,0
       0      .1       0      90     .07       0   258.1     .06       0
   418.1     .05       0  586.08    .045       0  597.78      .1       0
  694.82     .06       0  794.82      .1       0
Bank Sta=586.08,597.78
XS Rating Curve= 0 ,0
Exp/Cntr(USF)=0,0
Exp/Cntr=0.3,0.1
LCMann Table=0

Chan Stop Cuts=-1
Use User Specified Reach Order=0
Composite Channel Slope=5