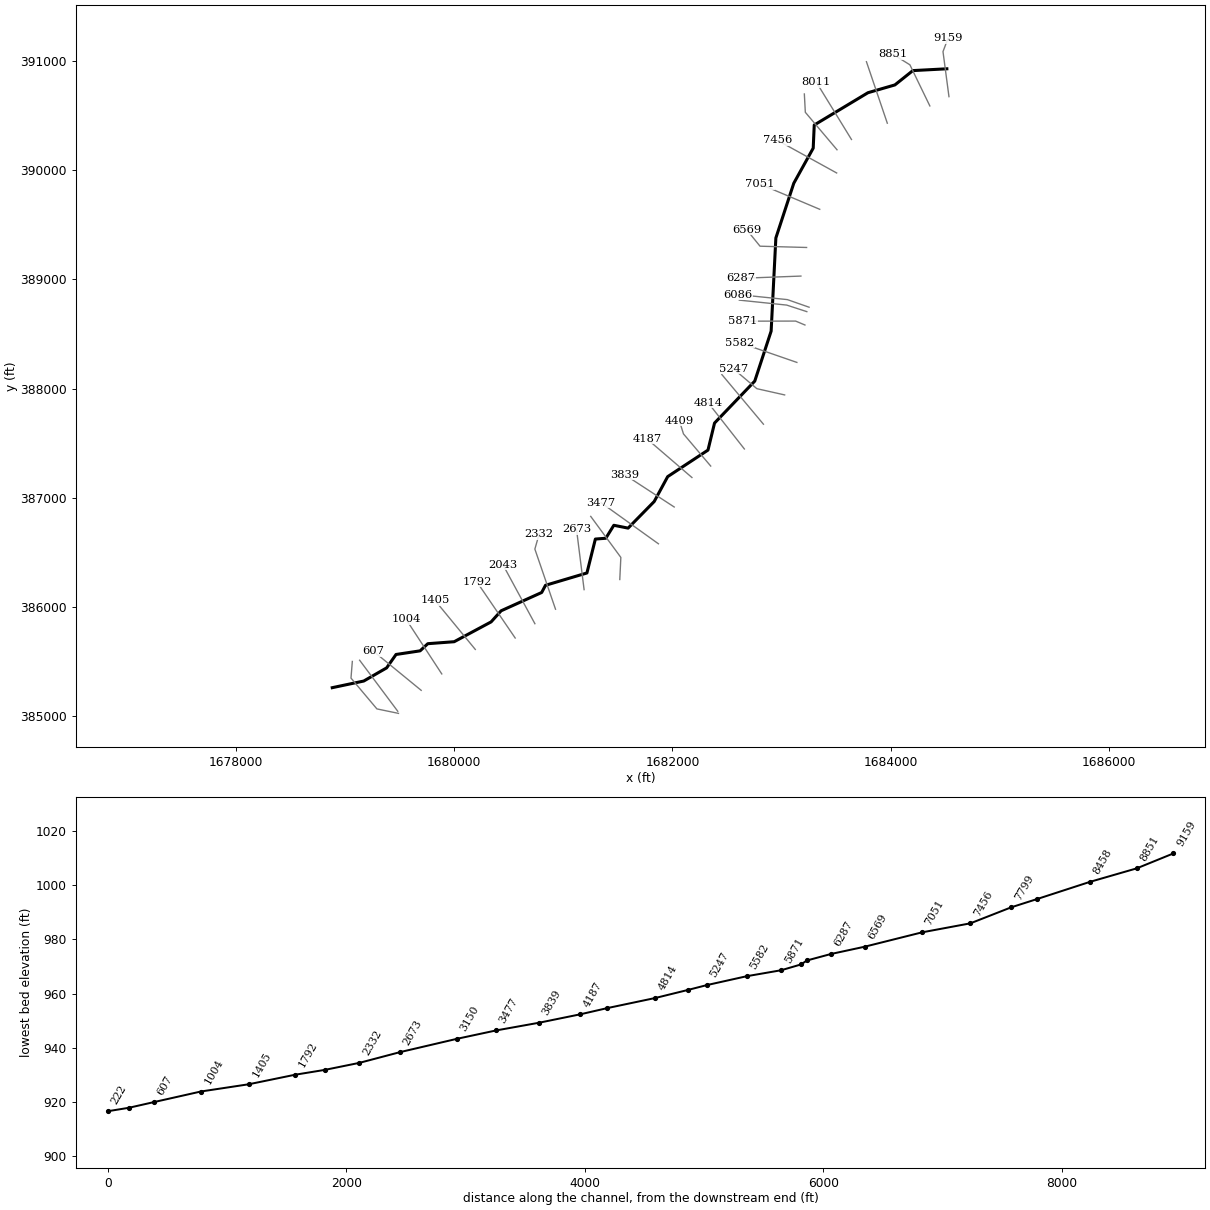
--- WILEYFK.prj (project) ---

Proj Title=WILEYFK
Current Plan=p01
Default Exp/Contr=0,0
English Units
Geom File=g01
Flow File=f01
Plan File=p01
BEGIN DESCRIPTION:
---------- MODELED AS PART OF WVEMD CTP PROGRAM, 2023----------
Stream Name: Wiley Fork
Flood Zone:  AFH
Wetzel County, WV
HEC-RAS Version: RAS 6.3
Vertical Datum: NAVD88
Projection: NAD 1983 StatePlane West Virginia S FIPS 4702 (US Feet)
Terrain: 1-meter West Virginia FEMA R3 South Central (collected 2018-2020)
Land Use: 2019 NLCD
Hydrologic Method:
WV 2010 Regional Regression Equations
Additional Model Notes:
KWSE tie-in with NFKFSHNGCK_M due to dominant flow path issue; 1 structure, IFAs used to resolve drawdown
END DESCRIPTION:
DSS Export Rating Curves= 0
DSS Export Rating Curve Sorted= 0
DSS Export Volume Flow Curves= 0
DXF OffsetX= 0
DXF OffsetY= 0
DXF ScaleX= 0
DXF ScaleY= 0

--- WILEYFK.p01 (plan) ---

Plan Title=Floodplain
Program Version=6.31
Short Identifier=Floodplain
Geom File=g01
Flow File=f01
Subcritical Flow
K Sum by GR= 0
Std Step Tol= 0.01
Critical Tol= 0.01
Num of Std Step Trials= 20
Max Error Tol= 0.3
Flow Tol Ratio= 0.001
Split Flow NTrial= 30
Split Flow Tol= 0.02
Split Flow Ratio= 0.02
Log Output Level= 0
Friction Slope Method= 1
Unsteady Friction Slope Method= 2
Unsteady Bridges Friction Slope Method= 1
Parabolic Critical Depth
Global Vel Dist= 0 , 0 , 0
Global Log Level= 0
CheckData=True
Encroach Param=-1 ,0,0, 0
Mapping Interval=1HOUR
Computation Time Step Use Courant=        0
Computation Time Step Use Time Series=    0
Computation Time Step Count To Double=0
Computation Time Step Max Doubling=0
Computation Time Step Max Halving=0
Computation Time Step Residence Courant=0
Run HTab= 0
Run UNet= 0
Run Sediment= 0
Run PostProcess= 0
Run WQNet= 0
Run RASMapper=-1
UNET Theta= 0
UNET Theta Warmup= 0
UNET ZTol= 0
UNET ZSATol= 0
UNET MxIter= 0
UNET Max Iter WO Improvement= 0
UNET MaxInSteps= 0
UNET DtIC= 0
UNET DtMin= 0
UNET MaxCRTS= 0
UNET WFStab= 0
UNET SFStab= 0
UNET WFX= 1
UNET SFX= 1
UNET Gravity=32.17405
UNET 1D Methodology=Finite Difference
UNET DSS MLevel= 1
UNET Pardiso=0
UNET DZMax Abort= 0
UNET Use Existing IB Tables= 0
UNET Froude Reduction=False
UNET Froude Limit= 0
UNET Froude Power= 0
UNET D1 Cores= 0
UNET WindReference=Eulerian
UNET WindDragFormulation=Hsu (1988)
UNET D2 Coriolis=0
UNET D2 Cores= 0
UNET D2 Theta= 1
UNET D2 Theta Warmup= 1
UNET D2 Z Tol= 0.01
UNET D2 Volume Tol= 0.01
UNET D2 Max Iterations= 20
UNET D2 Equation= 0
UNET D2 RampUpFraction=0.1
UNET D2 TimeSlices= 1
UNET D2 Turbulence Formulation=Non-Conservative (original)
UNET D2 Eddy Viscosity=0.3
UNET D2 Transverse Eddy Viscosity=0.1
UNET D2 Smagorinsky Mixing=0
UNET D2 BCVolumeCheck=0
UNET D2 Cores=0
UNET D2 SolverType=PARDISO (Direct)
UNET D2 Minimum Iterations= 3
UNET D2 Maximum Iterations= 30
UNET D2 Restart Number= 10
UNET D2 Relaxation Coeff=1.3
UNET D2 SOR Precondition Iterations= 10
UNET D2 ILUT Maximum Fill= 8
UNET D2 ILUT Tolerance=1E-08
UNET D2 Convergence Tolerance=0.00001
UNET D1D2 MaxIter= 0
UNET D1D2 ZTol=0.01
UNET D1D2 QTol=0.1
UNET D1D2 MinQTol=1
Write IC File= 0
Write IC File at Fixed DateTime=0
Write IC File at Sim End=0
Echo Input=False
Echo Parameters=False
Echo Output=False
Write Detailed= 0
HDF Write Warmup=0
HDF Write Time Slices=0
HDF Flush=0
HDF Compression= 1
HDF Chunk Size= 1
HDF Spatial Parts= 1
HDF Use Max Rows=0
HDF Fixed Rows= 1
Calibration Method= 0
Calibration Iterations= 20
Calibration Max Change=0.05
Calibration Tolerance=0.2
Calibration Maximum=1.5
Calibration Minimum=0.5
Calibration Optimization Method= 1
WQ AD Non Conservative
WQ ULTIMATE=-1
WQ Max Comp Step=1HOUR
WQ Output Interval=15MIN
WQ Output Selected Increments= 0
WQ Create Restart=0
WQ Fixed Restart=0
WQ System Summary=0
WQ Write To DSS=0
Sorting and Armoring Iterations= 10
XS Update Threshold= 0.02
Bed Roughness Predictor= 0
Hydraulics Update Threshold= 0.02
Energy Slope Method= 1
Volume Change Method= 1
Sediment Retention Method= 0
Sediment TS Multiplier= 1
Warm Up Method= 0
XS Weighting Method= 0
Number of US Weighted Cross Sections= 1
Number of DS Weighted Cross Sections= 1
Upstream XS Weight=0
Main XS Weight=1
Downstream XS Weight=0
Number of DS XS's Weighted with US Boundary= 1
Upstream Boundary Weight= 1
Weight of XSs Associated with US Boundary= 0
Number of US XS's Weighted with DS Boundary= 1
Downstream Boundary Weight= 0.5
Weight of XSs Associated with DS Boundary= 0.5
Percentile Method= 0
Sediment Output Level= 3
Mass or Volume Output= 0
Output Increment Type= 1
Profile and TS Output Increment= 1
Transport Output Increment 1
XS Output Flag= 0
XS Output Increment= 10
Read HDF5 Sediment Hotstart= 0
Sediment Hotstart Type= 0
Write Gradation File= 0
Read Gradation Hotstart= 0
Write HDF5 File= 1
Write Binary Output= 1
Write DSS Sediment File= 0
DSS Sediment Output Type= 1
SV Curve= 0
Specific Gage Flag= 0
Subcell Erosion Methods= 0
Subcell Deposition Methods= 0
Advection Scheme= 1
Matrix Solver= 0
Implicit Weighting Factor= 1
Maximum Outer Loop Convergence Iterations= 5
Convergence Maximum Absolute= 0.001
Convergence RMSE= 0.0001
Grain Fractions Max Abs Error= 0.001
Max Subgrid Regions= 1
Max Subgrid Length Scale= 3.402823E+38
Initial Layer Thickness= 3.402823E+38
Min Layer Thickness= 3.402823E+38
Max Layer Thickness= 3.402823E+38
Number of Layers= 5

--- WILEYFK.f01 (steady flow) ---

Flow Title=Flow
Program Version=6.31
Number of Profiles= 1
Profile Names=F01pct
River Rch & RM=WILEYFK,Main            ,9159
     729
River Rch & RM=WILEYFK,Main            ,6569
     815
River Rch & RM=WILEYFK,Main            ,5247
     968
River Rch & RM=WILEYFK,Main            ,3150
    1090
River Rch & RM=WILEYFK,Main            ,0
    1940
Boundary for River Rch & Prof#=WILEYFK,Main            , 1
Up Type= 0
Dn Type= 1
Dn Known WS=920.6
DSS Import GetInterval= 0
DSS Import GetPeak= 0
DSS Import FillOption= 0

--- WILEYFK.g01 (geometry) ---

Geom Title=Geometry
Program Version=6.31

River Reach=WILEYFK         ,Main
Reach XY= 30
1684513.55169726390930.0631415061684202.12299959390913.514001123
1684037.64532587390782.3111576281683790.66588259390710.874989821
1683298.71114388390414.9848626151683289.23999959390203.021001132
 1683111.2299996389881.4420011461682947.15099959389380.305001089
 1682903.8089996 388526.630001131682753.66199959388068.834001143
1682385.25799959387684.5640011021682325.27599958387436.898001111
1681956.09799958387193.8750011011681832.65199957386965.945001091
 1681593.4989996386722.148001132 1681462.7009996386748.076001133
1681389.17399961386629.2730011171681293.59099961386621.921001107
 1681216.1949996386311.177001125 1680836.5689996386198.179001138
1680801.74099959386132.3920011291680430.24099958385964.831001087
1680338.52699958385863.0550011221680000.27648069385681.489704621
1679758.44599961385663.3740011341679688.07866602385597.891074553
1679467.44586278385564.5702566831679381.33037023385441.761333943
1679171.78699958385321.2850011431678883.09490801385260.328097719

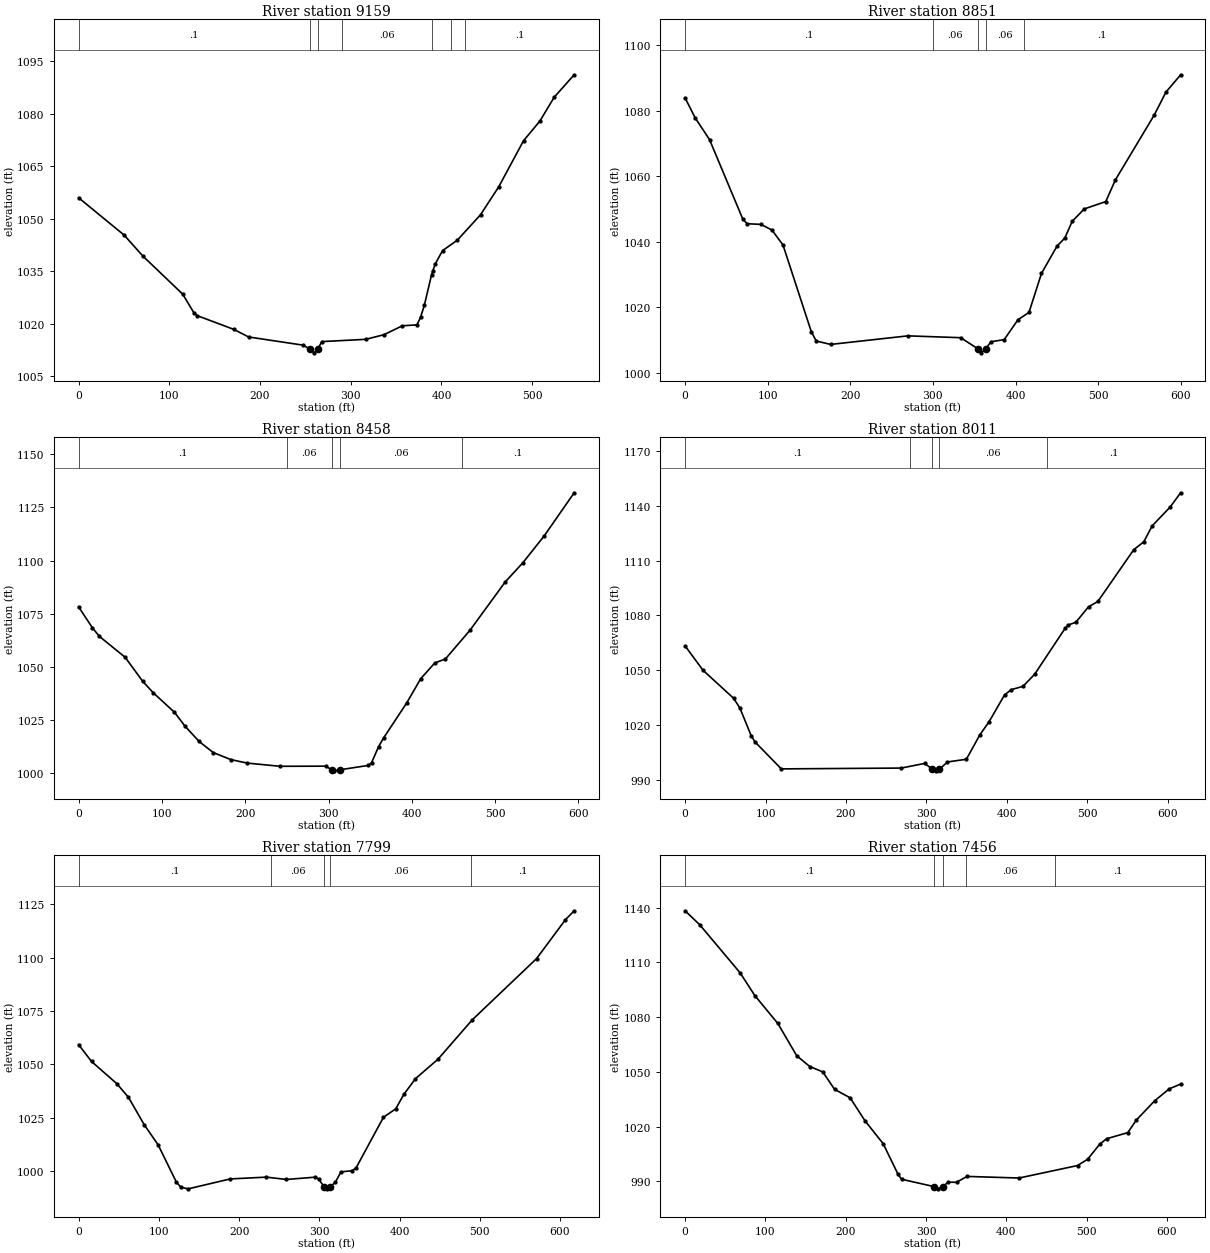
Type RM Length L Ch R = 1 ,9159    ,305.9,308.2,309.3
XS GIS Cut Line= 3
1684532.88950504390674.7750396871684478.21554703391087.314904609
1684524.19137535391209.088720158
#Sta/Elev= 30
       0 1055.94    50.2 1045.27    70.9 1039.27   114.8 1028.39   126.9 1023.15
   130.9 1022.25   171.2 1018.33   187.4 1016.17   247.9 1013.82  254.651012.729
     260 1011.64  263.671012.728   268.1 1014.85   316.5  1015.5   336.7 1016.83
   356.9 1019.37     373 1019.63     377 1021.83   381.1 1025.21   389.1 1033.96
   390.6 1035.13   393.2 1037.07   401.2 1040.84   417.5 1043.83   443.1  1051.1
   463.1 1059.06   490.5 1072.24   508.6 1077.89   524.3 1084.67 546.311 1091.08
#Mann= 7 ,-1,0
       0      .1       0  254.65    .045       0  263.67      .1       0
     290     .06       0     390      .1       0     410     .06       0
  426.15      .1       0
Bank Sta=254.65,263.67
XS Rating Curve= 0 ,0
Exp/Cntr(USF)=0,0
Exp/Cntr=0.3,0.1

Type RM Length L Ch R = 1 ,8851    ,393,393.3,391.4
XS GIS Cut Line= 3
1684357.68848033 390589.909245411684175.05761694390966.506143026
1684020.99237499391062.220253577
#Sta/Elev= 30
       0 1083.91    12.1 1077.85    29.6 1071.17    69.6 1047.09      75 1045.52
    91.8 1045.32   105.2 1043.58   118.5 1039.04   152.8 1012.57   158.8 1009.73
   176.3  1008.7   269.7 1011.31   333.6 1010.75  354.011007.433   358.6 1006.13
  364.081007.434   370.3 1009.51   386.3 1010.16     403 1016.24   416.3 1018.46
   431.4 1030.34   450.3 1038.71   459.7 1041.14   468.6 1046.24   483.2 1050.03
   509.3 1052.28   520.9 1058.89     568  1078.7   582.1 1085.67   599.9 1090.96
#Mann= 5 ,-1,0
       0      .1       0     300     .06       0  354.01    .045       0
  364.08     .06       0     410      .1       0
Bank Sta=354.01,364.08
XS Rating Curve= 0 ,0
Exp/Cntr(USF)=0,0
Exp/Cntr=0.3,0.1

Type RM Length L Ch R = 1 ,8458    ,444.1,446.1,445.2
XS GIS Cut Line= 2
1683968.08429849390431.6140366321683776.86801275390994.911783864
#Sta/Elev= 30
       0 1078.21    16.5 1068.43    24.8 1064.41    55.9  1054.5      77  1043.2
    89.7  1037.8     115  1028.7   127.7 1022.16   144.6 1014.96   161.5 1009.76
   182.6 1006.44   202.5 1004.78   241.8 1003.28   296.7 1003.34  303.84 1001.63
   306.6 1001.14   313.6 1001.64   347.4 1003.66   351.6 1004.87     360 1012.46
     366 1016.55   393.8 1033.03   410.7 1044.47   427.6 1051.88   440.3 1053.73
   469.9 1067.28   512.1 1089.94   533.2 1098.93   558.6 1111.44   594.9 1131.88
#Mann= 5 ,-1,0
       0      .1       0     250     .06       0  303.84    .045       0
   313.6     .06       0     460      .1       0
Bank Sta=303.84,313.6
XS Rating Curve= 0 ,0
Exp/Cntr(USF)=0,0
Exp/Cntr=0.3,0.1

Type RM Length L Ch R = 1 ,8011    ,211.5,212.3,212.8
XS GIS Cut Line= 2
1683639.71460934390282.5763602551683317.67424293390807.522816926
#Sta/Elev= 30
       0 1063.27    22.2 1049.95    60.4 1034.51    68.1 1029.21    82.1 1014.08
    86.8 1010.66   119.6  995.84   268.7  996.29   297.8  998.84   307.3  995.65
     312  994.77  316.08  995.62   326.1  999.64   349.6 1001.12   366.4 1014.54
   377.7 1021.62     397 1036.37   405.4  1039.3     420 1041.09   434.5 1047.75
   472.3  1072.9   476.3 1074.75   485.7 1076.24   501.4 1084.69     513 1087.62
   557.6 1116.01   570.1 1120.34   580.6 1129.12     603 1139.46   615.9 1147.22
#Mann= 5 ,-1,0
       0      .1       0     280     .06       0   307.3    .045       0
  316.08     .06       0     450      .1       0
Bank Sta=307.3,316.08
XS Rating Curve= 0 ,0
Exp/Cntr(USF)=0,0
Exp/Cntr=0.3,0.1

Type RM Length L Ch R = 1 ,7799    ,340.7,343.1,341.8
XS GIS Cut Line= 3
 1683507.2742668390188.2219792131683217.04054297390531.447815548
1683208.07264701390699.392049003
#Sta/Elev= 30
       0 1059.27    16.1  1051.4    47.6 1041.01    62.1 1034.64    81.9  1021.7
      99 1012.45   121.7  995.04   127.4  992.53   136.6  991.79     189  996.43
   234.1  997.27   258.9  996.18   294.8  997.25     299  996.48  305.85  992.83
   309.5  991.86  313.79   992.8     320  994.85     327  999.71   340.9 1000.29
   345.9 1001.65     380 1025.31   395.2  1029.2   405.5 1036.07   419.9 1043.36
   448.1 1052.53   490.6 1070.87   570.8 1099.55   606.8 1117.76   617.7 1121.94
#Mann= 5 ,-1,0
       0      .1       0     240     .06       0  305.85    .045       0
  313.79     .06       0  489.49      .1       0
Bank Sta=305.85,313.79
XS Rating Curve= 0 ,0
Exp/Cntr(USF)=0,0
Exp/Cntr=0.3,0.1

Type RM Length L Ch R = 1 ,7456    ,404.3,405.2,405.1
XS GIS Cut Line= 2
1683504.11350259 389975.686226011682963.80355959390273.579987168
#Sta/Elev= 30
       0 1138.31    18.3 1130.61    68.5 1104.29    86.8 1091.84   115.5 1076.52
     139 1058.82   155.3 1052.92   171.4    1050   186.1 1040.43   205.5 1035.78
   223.8 1023.31   246.7 1010.58   264.9  994.07   269.5  991.13   309.9  987.12
   315.2  985.88  321.15987.1205   327.4  989.54     338  989.48     351  992.69
   415.8  991.81   488.7  998.66   501.2  1002.1   516.1 1010.26   524.7 1013.34
   551.2 1016.69   561.8 1023.56   584.7 1034.16   602.9 1040.71     617  1043.3
#Mann= 5 ,-1,0
       0      .1       0   309.9    .045       0  321.15      .1       0
     350     .06       0     460      .1       0
Bank Sta=309.9,321.15
XS Rating Curve= 0 ,0
Exp/Cntr(USF)=0,0
Exp/Cntr=0.3,0.1

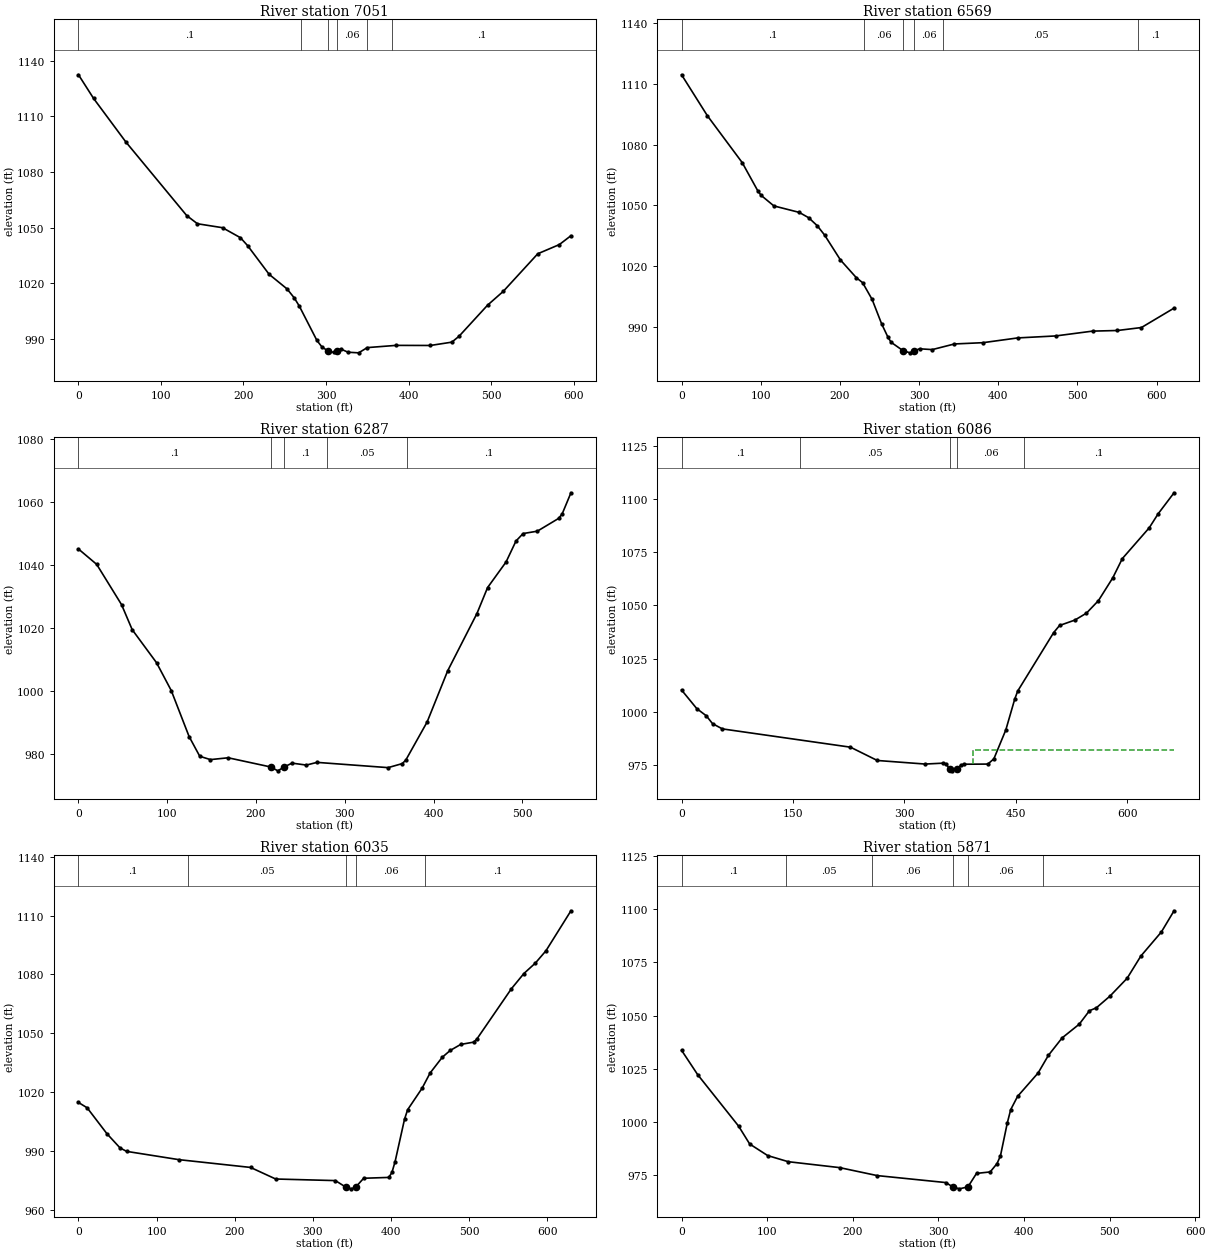
Type RM Length L Ch R = 1 ,7051    ,479.5,482,484.3
XS GIS Cut Line= 2
1683348.99832726389642.8361699281682799.10463612389874.955869043
#Sta/Elev= 30
       0 1132.42    18.3 1119.68    57.4 1096.22   131.2 1056.53   144.2 1052.13
   174.6    1050   196.3 1044.61     205 1040.34   231.1 1024.87   252.8 1017.01
   261.5 1012.19   267.6 1007.79     289  989.23   295.1  985.73   302.7  983.48
   309.2  982.84     313  983.47   317.9  984.64   326.6   982.9   339.6  982.56
     350  985.38   384.9  986.58   426.5  986.53   452.5  988.32   461.2  991.47
   495.9 1008.28   514.9 1015.71   556.7 1035.96   582.8  1040.9   596.9 1045.69
#Mann= 6 ,-1,0
       0      .1       0     270     .06       0   302.7    .045       0
     313     .06       0     350     .05       0     380      .1       0
Bank Sta=302.7,313
XS Rating Curve= 0 ,0
Exp/Cntr(USF)=0,0
Exp/Cntr=0.3,0.1

Type RM Length L Ch R = 1 ,6569    ,280.4,281.5,281.2
XS GIS Cut Line= 3
1683228.69172471389293.1061336331682802.12525429389304.800055517
1682679.05879501389456.500385828
#Sta/Elev= 30
       0 1114.41    32.6 1094.21    76.6 1071.09    96.6 1056.95   100.6  1054.9
   116.6 1049.73   148.6 1046.54   160.6 1043.89   171.4 1039.96   180.6  1035.4
   200.7 1023.07   220.7 1014.35   228.7 1011.86   240.7 1003.61   252.7  991.57
   260.7  984.98   264.7  982.46  279.86978.3039   288.7  977.26  294.08978.3016
   300.7  979.25   316.7  978.86   344.7  981.64   380.7  982.27   424.7  984.62
   472.7   985.6   519.1  987.97   550.6  988.28   580.9  989.74   622.1  999.32
#Mann= 6 ,-1,0
       0      .1       0     230     .06       0  279.86    .045       0
  294.08     .06       0     330     .05       0  576.73      .1       0
Bank Sta=279.86,294.08
XS Rating Curve= 0 ,0
Exp/Cntr(USF)=0,0
Exp/Cntr=0.3,0.1

Type RM Length L Ch R = 1 ,6287    ,203.8,201.8,200.6
XS GIS Cut Line= 2
1683176.58175987389031.1746733711682622.22867954 389010.57402271
#Sta/Elev= 30
       0  1045.1    20.5 1040.23    48.5 1027.43    60.5 1019.47    87.9 1008.97
   104.5 1000.11   124.6  985.49   136.6  979.22   148.6  978.16   168.6  978.74
  216.45975.8228   224.6  974.59  231.71  975.85   240.6  977.04   256.6  976.42
   268.7  977.28   348.7  975.61   364.7  976.89   368.7  978.02   392.7  990.12
   415.9 1006.42   448.8 1024.59   460.8 1032.85   481.6 1040.98   492.8 1047.65
   500.8 1050.02   516.8 1050.77   540.8 1054.83   544.8 1056.26   554.7 1062.98
#Mann= 5 ,-1,0
       0      .1       0  216.45    .045       0  231.71      .1       0
     280     .05       0     370      .1       0
Bank Sta=216.45,231.71
XS Rating Curve= 0 ,0
Exp/Cntr(USF)=0,0
Exp/Cntr=0.3,0.1

Type RM Length L Ch R = 1 ,6086    ,50.3,50.4,50.3
XS GIS Cut Line= 3
1683251.44952185388745.8763169611683052.41491605388815.531768093
1682602.89361163 388861.68612836
#Sta/Elev= 30
       0 1010.19    20.5 1001.44    33.2   998.1    41.7  994.38    54.9  991.92
   227.3  983.32   263.4  977.07   327.8  975.39   351.9  975.81   355.9  975.53
   360.7973.0363     364   972.2  371.35973.0373   375.9  974.96   379.8  975.31
   412.2  975.38   420.3  977.84   436.4  991.44   448.4 1005.94   452.4 1009.72
   500.7 1037.15   508.7 1040.53   529.3 1043.07   544.9 1046.33     561  1052.2
   580.4 1062.97   593.2 1071.98   629.4 1086.45   641.4 1093.04   662.8 1102.92
#Mann= 5 ,-1,0
       0      .1       0     160     .05       0   360.7    .045       0
  371.35     .06       0  460.87      .1       0
#XS Ineff= 2 , 0
                          392.36          982.03
Permanent Ineff=
       F       F
Bank Sta=360.7,371.35
XS Rating Curve= 0 ,0
Exp/Cntr(USF)=0,0
Exp/Cntr=0.3,0.1

Type RM Length L Ch R = 1 ,6035    ,164,164.7,165.2
XS GIS Cut Line= 3
1683230.68700336  388705.34225931683046.26477856388765.363960102
1682612.23347626  388810.7030571
#Sta/Elev= 30
       0 1014.73    11.1 1012.02    36.4  998.83    53.2  991.58    61.6  989.82
   128.9  985.58   220.2  981.64   252.4  975.74   328.8  974.93  342.43971.5276
   348.9  970.73  354.59971.5288     365  976.12   397.2  976.55   401.2   979.1
   405.2  984.56   417.3 1006.21   421.3 1011.07   439.8 1022.01     450 1029.73
   465.6 1037.77   475.7 1041.22   489.2 1044.31   505.8 1045.48   509.8 1047.02
     554 1072.64   570.1 1080.45   584.8 1085.78   598.3 1092.03   630.3 1112.41
#Mann= 5 ,-1,0
       0      .1       0     140     .05       0  342.43    .045       0
  354.59     .06       0  443.94      .1       0
Bank Sta=342.43,354.59
XS Rating Curve= 0 ,0
Exp/Cntr(USF)=0,0
Exp/Cntr=0.3,0.1

Type RM Length L Ch R = 1 ,5871    ,291.5,288.8,285.7
XS GIS Cut Line= 3
1683213.45686712388582.8968005321683128.17684662388618.840185998
1682645.29778726388617.983675373
#Sta/Elev= 30
       0 1033.67    18.8 1022.24    66.6  998.08    79.6  989.66   100.6  984.23
   124.6  981.36   184.6  978.58   228.6  974.83   308.6  971.56  316.85969.5431
   324.6  968.61  334.61 969.544   344.6  975.86   360.6  976.55   368.6  980.49
   372.6  984.15   380.6   999.6   384.6 1005.85   392.6 1012.03   416.6 1023.04
   428.6  1031.3   444.6 1039.48   464.6 1045.92   476.6 1052.27   484.6 1053.61
   500.6 1059.14   520.6  1067.5   536.6 1077.92   560.6 1089.24   575.4 1099.19
#Mann= 6 ,-1,0
       0      .1       0  122.55     .05       0  222.55     .06       0
  316.85    .045       0  334.61     .06       0  422.55      .1       0
Bank Sta=316.85,334.61
XS Rating Curve= 0 ,0
Exp/Cntr(USF)=0,0
Exp/Cntr=0.3,0.1

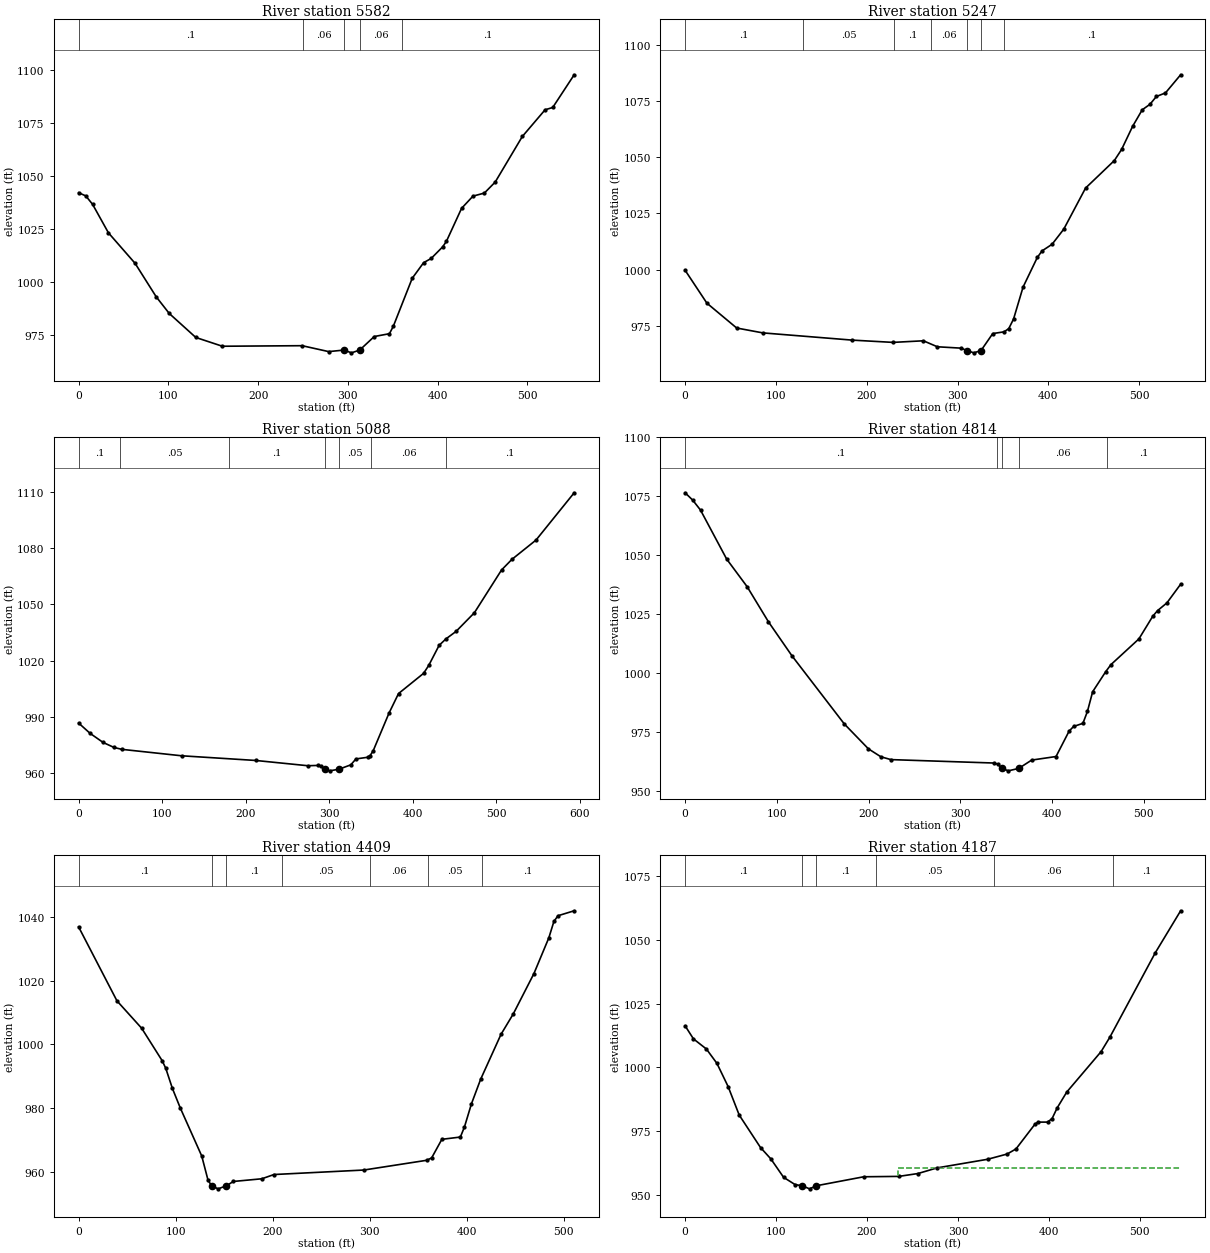
Type RM Length L Ch R = 1 ,5582    ,335.9,334.4,329.8
XS GIS Cut Line= 2
1683139.53567309388240.2659191921682617.56177306388420.663627615
#Sta/Elev= 30
       0 1042.14     7.9 1040.66    15.5  1036.7    33.2 1023.18    62.9 1008.76
    86.5  992.89     101  985.03   130.6  973.68   160.2  969.53   249.1  969.79
   278.7  966.99   295.6  967.72   304.1  966.41  313.24  967.71   329.5  974.13
   346.4  975.46   350.7  978.95   371.8 1001.68   384.5 1009.06   392.9 1011.05
   405.7 1016.52   409.9 1019.14   426.8 1034.75   439.5 1040.53   452.2 1041.98
   464.3 1047.19   494.5 1068.74   519.9 1081.38   528.4 1082.46   552.3 1097.93
#Mann= 5 ,-1,0
       0      .1       0     250     .06       0   295.6    .045       0
  313.24     .06       0     360      .1       0
Bank Sta=295.6,313.24
XS Rating Curve= 0 ,0
Exp/Cntr(USF)=0,0
Exp/Cntr=0.3,0.1

Type RM Length L Ch R = 1 ,5247    ,161.3,159.8,158.1
XS GIS Cut Line= 3
1683027.53667291387942.3866027031682772.92995394387999.618084201
1682555.74381902388183.786056714
#Sta/Elev= 30
       0   999.8      24  985.19    56.8  974.16    85.5     972   183.9  968.79
     229  967.78   262.4  968.49   277.8  965.83     304  965.22  310.26964.1638
     318  963.14  325.88964.1625   338.8   971.7   351.2  972.46   356.4  973.89
   361.7  978.14   372.2  992.35   387.9 1005.51   393.1  1008.4   404.1 1011.32
     417 1018.04     441 1036.28   472.7  1048.5   480.7 1053.43   492.8 1063.67
   503.4 1071.02   511.9 1073.46     519 1076.93     529 1078.52   545.7 1086.57
#Mann= 7 ,-1,0
       0      .1       0     130     .05       0     230      .1       0
  270.96     .06       0  310.26    .045       0  325.88     .06       0
  350.96      .1       0
Bank Sta=310.26,325.88
XS Rating Curve= 0 ,0
Exp/Cntr(USF)=0,0
Exp/Cntr=0.3,0.1

Type RM Length L Ch R = 1 ,5088    ,272.3,273.3,271.3
XS GIS Cut Line= 2
1682833.47609292387674.0626326151682452.23474005388129.036761915
#Sta/Elev= 30
       0  986.79    13.7  981.31    29.3  976.46    42.5  973.77    51.9  972.78
   123.3  969.36     212  966.87   274.6  964.06   286.7  964.22   290.3  963.93
  294.77962.2421   300.9  961.34   312.1962.2446     326  964.53   332.2  967.68
   346.3  968.57   349.1  969.41   352.9  972.08   371.8  992.08   383.2 1002.49
   413.2 1013.25   419.4 1017.49   431.8 1028.15     440 1031.61     452 1035.54
   474.1 1045.54   506.6  1068.3     519 1073.94   547.9 1084.23   593.6 1109.41
#Mann= 7 ,-1,0
       0      .1       0      50     .05       0     180      .1       0
  294.77    .045       0   312.1     .05       0     350     .06       0
     440      .1       0
Bank Sta=294.77,312.1
XS Rating Curve= 0 ,0
Exp/Cntr(USF)=0,0
Exp/Cntr=0.3,0.1

Type RM Length L Ch R = 1 ,4814    ,405.4,405.3,407.2
XS GIS Cut Line= 2
1682658.54306961387447.3347012621682325.28044379 387872.30046573
#Sta/Elev= 30
       0 1076.46     8.3 1073.34    16.8 1069.11    45.3 1048.31    67.6 1036.59
    90.9 1021.63   116.5 1007.21   173.5   978.3   199.8  967.72   213.4  964.35
   224.3  963.15     337  961.69     341  961.15   345.4959.4167   352.3  958.38
  363.64959.4172   377.7  962.94   404.3  964.46   418.5  975.22   423.4  977.21
   433.6  978.56   438.5   983.6   444.2  991.97   458.4 1000.47   464.1 1003.47
   494.6  1014.4   509.7 1024.02   514.9 1026.41   525.1 1029.68   540.1 1037.63
#Mann= 5 ,-1,0
       0      .1       0     340     .06       0   345.4    .045       0
  363.64     .06       0     460      .1       0
Bank Sta=345.4,363.64
XS Rating Curve= 0 ,0
Exp/Cntr(USF)=0,0
Exp/Cntr=0.3,0.1

Type RM Length L Ch R = 1 ,4409    ,221.8,222.5,224.1
XS GIS Cut Line= 3
1682350.11206394387290.8099994031682100.65544991387585.424303466
1682063.38390306387704.534867262
#Sta/Elev= 30
       0 1036.95    39.5 1013.72      65  1005.1    86.1  994.91    89.8  992.53
    96.6  986.24   104.8  980.04   126.9  964.95   133.3  957.44  136.98955.5919
   143.8  954.63   152.3955.5942   159.5  956.95   188.8  957.79   201.4  959.13
     294  960.54   358.7   963.6   363.9  964.36   374.4  970.19   393.5  970.91
   397.7  974.07   404.9  981.35   414.4  989.08   435.4  1003.2     448  1009.6
   469.3 1022.28   484.7 1033.54   489.9 1038.67   494.1 1040.47   510.8 1042.03
#Mann= 7 ,-1,0
       0      .1       0  136.98    .045       0   152.3      .1       0
     210     .05       0     300     .06       0     360     .05       0
  416.04      .1       0
Bank Sta=136.98,152.3
XS Rating Curve= 0 ,0
Exp/Cntr(USF)=0,0
Exp/Cntr=0.3,0.1

Type RM Length L Ch R = 1 ,4187    ,346,347.8,348.4
XS GIS Cut Line= 2
1682178.27052588387185.7185253641681765.18894973387540.866687269
#Sta/Elev= 30
       0  1016.3     9.2 1011.17    23.4 1007.21      35 1001.57    47.3  992.48
    59.5   981.3    82.9  968.58    94.3  964.11   108.3  956.89   120.9  954.05
   128.8953.5782   136.8  952.38  144.15953.5777   196.4  957.11   234.9  957.26
     256  958.38   277.1   960.6   332.6  963.97   354.1  966.03   363.8  968.03
   384.7  977.76   387.9  978.54   398.5  978.55   403.5  979.95   409.1  984.14
   419.6  990.33   457.4  1006.2   467.1 1011.91   516.9 1044.92   544.8  1061.4
#Mann= 6 ,-1,0
       0      .1       0   128.8    .045       0  144.15      .1       0
     210     .05       0     340     .06       0     470      .1       0
#XS Ineff= 2 , 0
                          234.53           960.5
Permanent Ineff=
       F       F
Bank Sta=128.8,144.15
XS Rating Curve= 0 ,0
Exp/Cntr(USF)=0,0
Exp/Cntr=0.3,0.1

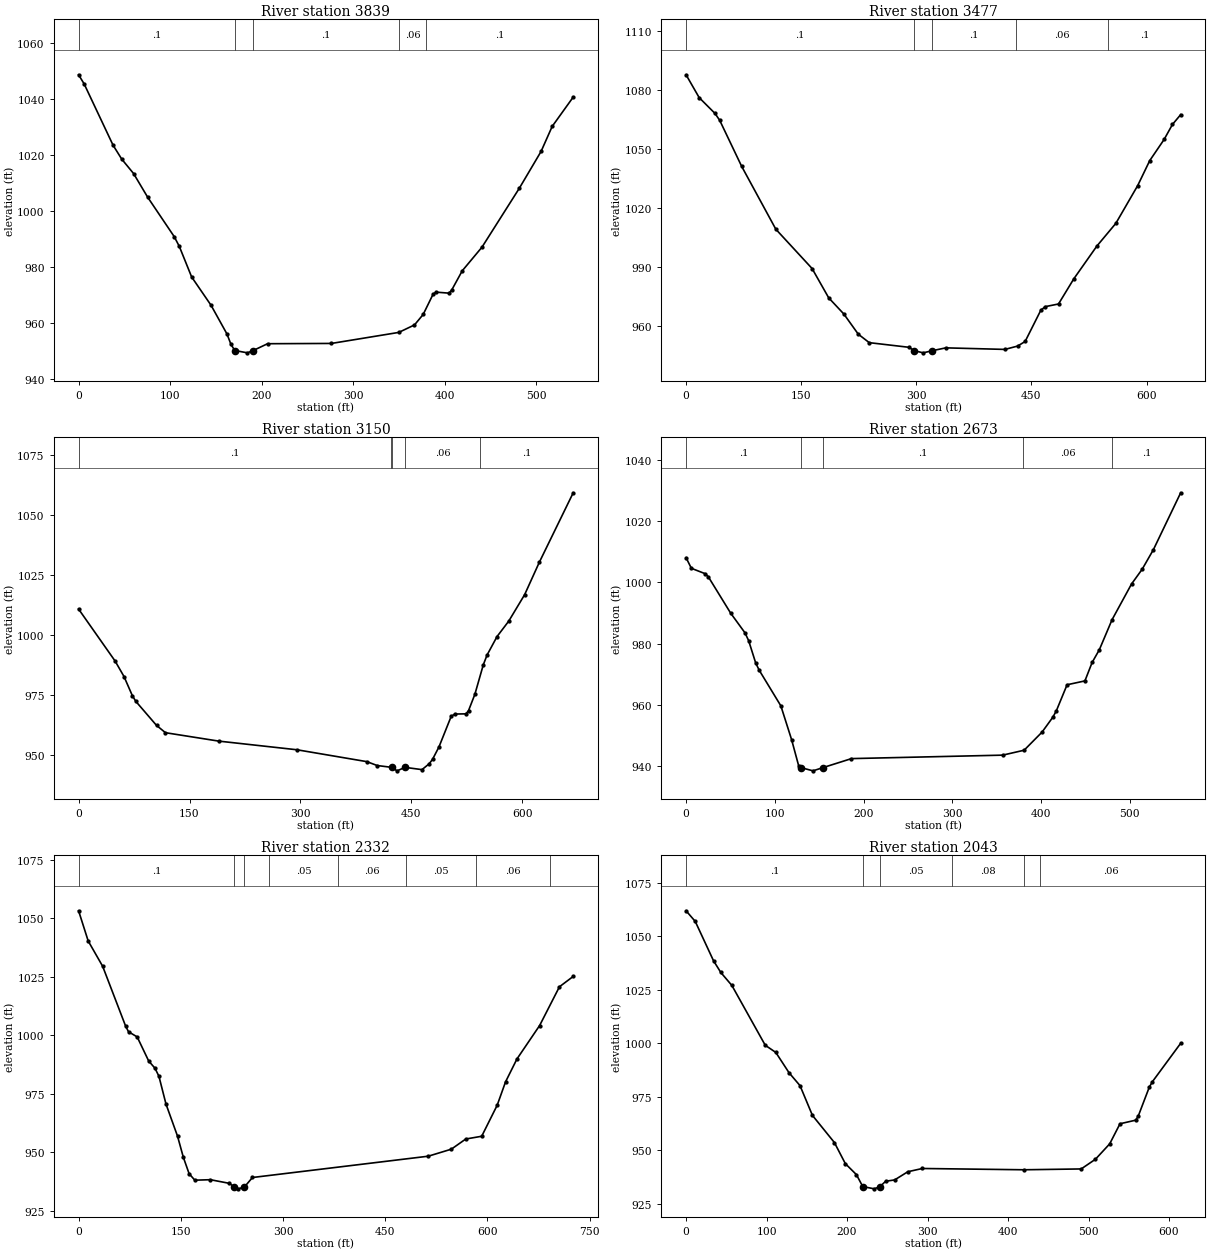
Type RM Length L Ch R = 1 ,3839    ,361.5,361.4,361.1
XS GIS Cut Line= 2
1682015.69508458386915.7196811171681562.77104613387210.959054326
#Sta/Elev= 30
       0 1048.64     6.1 1045.36    37.7 1023.46    47.2 1018.48    60.1 1013.35
    75.4 1004.94   104.5  990.81   110.1  987.31   123.6  976.37   144.8  966.26
   162.2     956   166.6  952.27  170.75950.0938   184.6  949.26   190.9950.0933
   206.6  952.52   276.4  952.62     350  956.56   367.2  959.24   376.7  962.98
   387.6  970.27     391  970.95     405  970.59   407.9  971.72   419.4  978.58
     441  987.04   481.8 1008.09   505.6 1021.26   517.7 1030.18   540.7 1040.66
#Mann= 5 ,-1,0
       0      .1       0  170.75    .045       0   190.9      .1       0
     350     .06       0     380      .1       0
Bank Sta=170.75,190.9
XS Rating Curve= 0 ,0
Exp/Cntr(USF)=0,0
Exp/Cntr=0.3,0.1

Type RM Length L Ch R = 1 ,3477    ,331.1,327.4,319.6
XS GIS Cut Line= 2
1681871.25193892386578.5791750851681347.37629646386954.031337092
#Sta/Elev= 30
       0 1087.57    17.1 1075.97    37.7 1067.95    43.8 1064.48    72.5 1041.04
     117 1009.15   164.2  989.22   185.9  974.31   205.6  966.12   224.4  955.88
   238.7  951.58   290.3  949.23   297.5947.4836     309  946.41  320.63947.4854
   338.5  948.94   415.4  948.15     432  949.84   441.8  952.17   462.3  968.07
   468.1  969.87   485.3  971.21   505.3  984.02   535.3 1000.62     560 1012.14
   588.5 1031.33   604.2 1044.02   622.9 1054.73   633.8 1062.37   644.5 1067.33
#Mann= 5 ,-1,0
       0      .1       0   297.5    .045       0  320.63      .1       0
     430     .06       0     550      .1       0
Bank Sta=297.5,320.63
XS Rating Curve= 0 ,0
Exp/Cntr(USF)=0,0
Exp/Cntr=0.3,0.1

Type RM Length L Ch R = 1 ,3150    ,487.9,477,470.4
XS GIS Cut Line= 3
1681517.28766503386251.2206734791681526.98445544386453.848994998
1681251.14619281386829.514262591
#Sta/Elev= 30
       0 1010.69    49.4  989.04    61.4  982.61    72.7  974.64    77.4  972.26
   105.4  962.25   117.5  959.21   189.5  955.71   295.4   952.1     390  947.15
   403.7  945.55  423.51  944.78   430.7  943.33   441.5  944.78   464.4  943.83
   474.2  946.29   478.7  948.14   487.3  953.24   503.9  966.03   508.9  966.98
   523.8  967.06   527.3  968.38   535.9  975.18   547.3  987.47   552.4  991.55
   565.9  999.25   581.7 1005.66   603.2 1016.68     623 1030.13   668.9 1059.11
#Mann= 5 ,-1,0
       0      .1       0  422.86     .06       0  423.51    .045       0
   441.5     .06       0  542.86      .1       0
Bank Sta=423.51,441.5
XS Rating Curve= 0 ,0
Exp/Cntr(USF)=0,0
Exp/Cntr=0.3,0.1

Type RM Length L Ch R = 1 ,2673    ,336.8,340.6,342.2
XS GIS Cut Line= 2
1681190.36683674386158.6096217881681120.78179928386711.562151579
#Sta/Elev= 30
       0 1008.11       6 1004.64    21.6 1002.87    25.2 1001.81    50.3  989.96
    66.4  983.54    70.5     981    78.5  973.65    82.5  971.28   106.8  959.68
   118.9  948.64   126.9  940.06  129.46939.4861     143  938.43  154.25939.4855
   186.4  942.43   356.7  943.56   380.9  945.17   401.1  951.09   413.2  955.94
   417.2  958.05   429.3  966.57   449.4  967.83   457.5  973.85   465.6  977.99
     480  987.85   501.9   999.5   513.9 1004.33   526.6 1010.76   557.3 1029.33
#Mann= 5 ,-1,0
       0      .1       0  129.46    .045       0  154.25      .1       0
     380     .06       0     480      .1       0
Bank Sta=129.46,154.25
XS Rating Curve= 0 ,0
Exp/Cntr(USF)=0,0
Exp/Cntr=0.3,0.1

Type RM Length L Ch R = 1 ,2332    ,285.5,289,288.1
XS GIS Cut Line= 3
 1680928.5270011 385979.175586691680739.30668323386530.144018209
1680778.62642943386667.962519643
#Sta/Elev= 30
       0 1053.15    14.1 1040.25    35.3 1029.48    69.1 1003.87    73.3 1001.52
      86  999.31   102.9  989.03   112.1  985.96   117.9  982.53   128.3  970.63
   145.2  956.97   153.7  947.98   162.2  940.94   170.6  938.17   193.4  938.38
   221.4  936.82  228.46935.2496   234.1  934.48  243.28935.2499   255.2  939.32
   513.2  948.41     547   951.4   568.2  955.74   591.6  956.92   614.3  970.14
   626.6  980.14   643.3  989.89   676.6 1004.17   705.7 1020.72   725.9 1025.13
#Mann= 8 ,-1,0
       0      .1       0  228.46    .045       0  243.28      .1       0
     280     .05       0     380     .06       0     480     .05       0
  582.56     .06       0  692.56      .1       0
Bank Sta=228.46,243.28
XS Rating Curve= 0 ,0
Exp/Cntr(USF)=0,0
Exp/Cntr=0.3,0.1

Type RM Length L Ch R = 1 ,2043    ,249.4,251,251.2
XS GIS Cut Line= 2
1680739.56834685385846.5383038881680446.76315818386386.754086962
#Sta/Elev= 30
       0 1061.85    11.4 1056.89    34.1  1038.5    43.2 1033.01    56.9 1026.96
    98.4  998.99   111.5  995.65   127.9  986.18   141.6  980.11     157  966.23
   184.3  953.53   197.9  943.67   211.6  938.56  219.55  932.96   233.9   931.9
  240.88932.9601     248  935.45   259.1  936.06   275.5  939.89   293.5  941.41
     420  940.81   490.9   941.2   508.6  945.73   526.3  952.92   539.1  962.31
   558.7     964   561.9  966.02   575.5  979.42   579.4  981.99   614.5  999.92
#Mann= 6 ,-1,0
       0      .1       0  219.55    .045       0  240.88     .05       0
     330     .08       0     420     .07       0     440     .06       0
Bank Sta=219.55,240.88
XS Rating Curve= 0 ,0
Exp/Cntr(USF)=0,0
Exp/Cntr=0.3,0.1

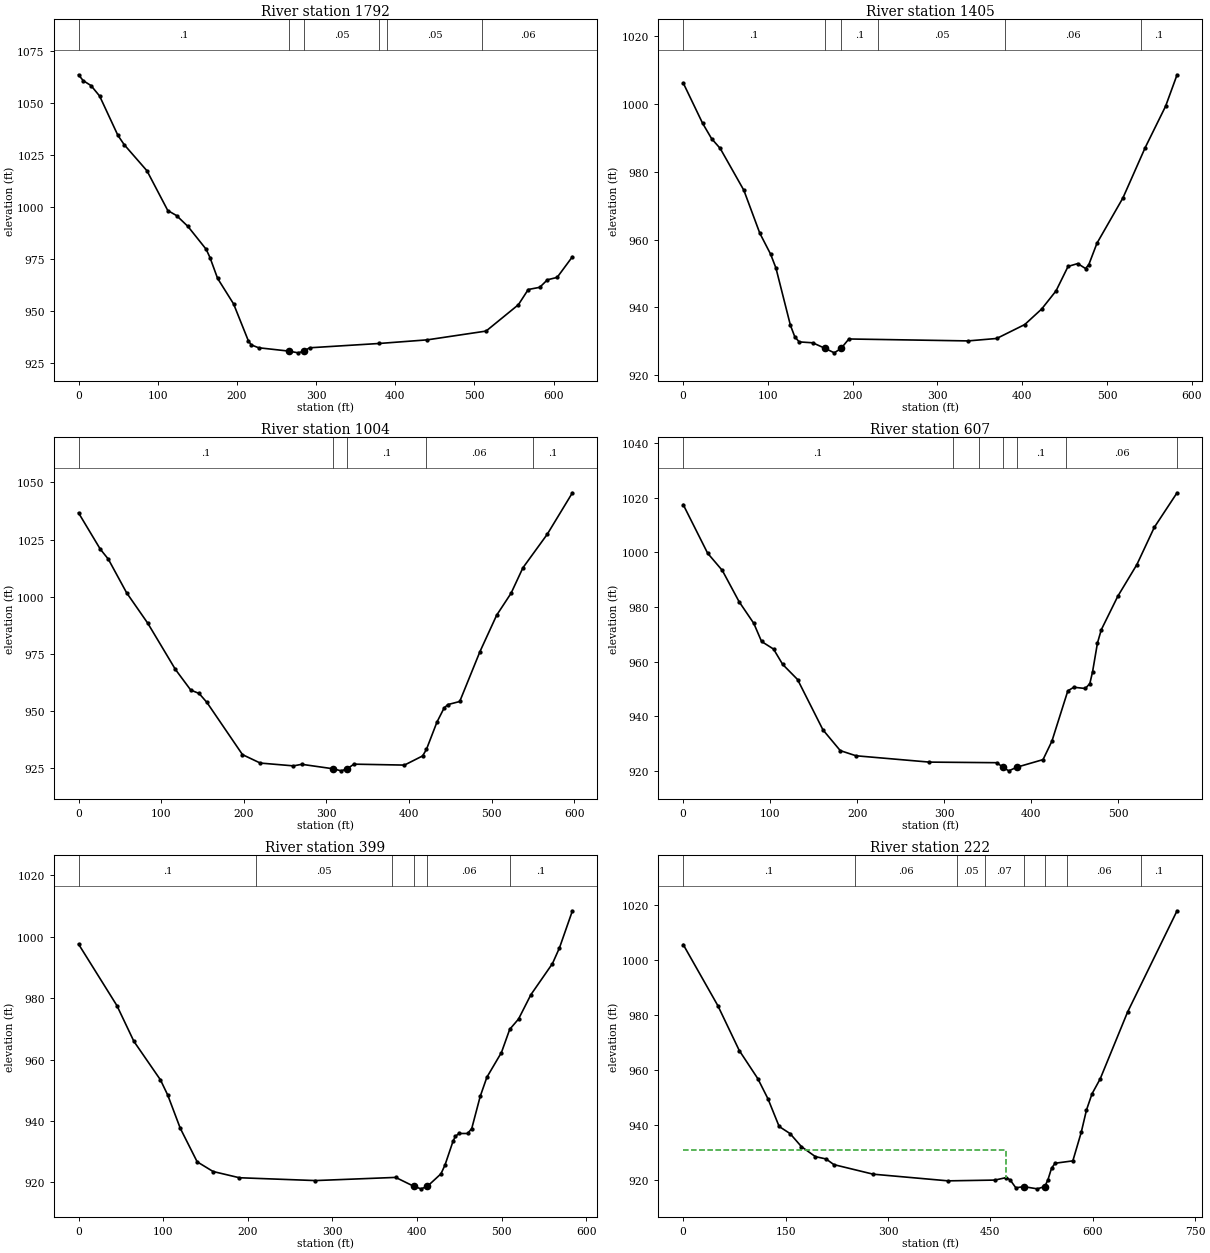
Type RM Length L Ch R = 1 ,1792    ,386.2,387.1,388.1
XS GIS Cut Line= 2
1680559.09466423385715.4580974781680207.35027436386230.596531284
#Sta/Elev= 30
       0 1063.52     5.8 1060.73    15.8 1058.32    26.6 1053.33    49.7 1034.45
    57.6 1030.01    86.4 1017.46   112.7  998.39   123.8  995.96   138.2  990.74
   161.2  979.78     166  975.83   175.6  965.84   195.8  953.59   214.4  935.94
   218.1  933.93   227.4  932.54   265.3930.9434   277.4   930.1  284.44930.9434
   291.9  932.52     380   934.6   440.4  936.33   514.7  940.54   555.5  953.17
     568  960.49   582.5  961.54   592.2  965.15   604.5   966.3   623.8  976.22
#Mann= 6 ,-1,0
       0      .1       0   265.3    .045       0  284.44     .05       0
     380      .1       0     390     .05       0     510     .06       0
Bank Sta=265.3,284.44
XS Rating Curve= 0 ,0
Exp/Cntr(USF)=0,0
Exp/Cntr=0.3,0.1

Type RM Length L Ch R = 1 ,1405    ,401.3,401.6,398.7
XS GIS Cut Line= 2
1680193.56873412385610.8125452551679823.55305876386060.906239916
#Sta/Elev= 30
       0 1006.26    22.9  994.34    33.5  989.81    43.7  986.91    71.6  974.56
    90.4   961.9   103.1  955.74   109.4  951.65   126.5  934.75   131.7  931.32
   136.9  929.83   152.9  929.56  167.28927.9317   178.3   926.6  186.35 927.933
   195.5  930.69   336.1  930.12   369.9  930.84     403  934.95   422.9  939.52
   439.9  944.88   454.1   952.1   465.5  952.94   474.7  951.48   478.6  952.65
   488.2  958.95   518.8   972.3   545.1  987.16   569.2  999.39   582.7 1008.65
#Mann= 6 ,-1,0
       0      .1       0  167.28    .045       0  186.35      .1       0
     230     .05       0     380     .06       0     540      .1       0
Bank Sta=167.28,186.35
XS Rating Curve= 0 ,0
Exp/Cntr(USF)=0,0
Exp/Cntr=0.3,0.1

Type RM Length L Ch R = 1 ,1004    ,391.1,396.8,395.5
XS GIS Cut Line= 2
1679886.44076418 385386.43580257 1679559.4175548385886.752746024
#Sta/Elev= 30
       0 1036.63    26.3 1020.79      36 1016.44    58.1 1001.77    83.7  988.46
   117.2  968.25   135.8  959.21   145.9  957.74   155.4   953.8   198.4  931.01
   219.9  927.33   260.1   926.1   270.1  926.78  307.45 924.865   317.9  923.93
  325.36924.8651   333.2  926.85   394.4  926.44   416.4  930.45     421  933.28
   433.8  945.27   442.4  951.39   446.9  952.87   461.3  954.23   485.8  976.03
     506  991.93   523.4  1001.5   537.8 1012.66   567.2 1027.28   597.7 1045.42
#Mann= 5 ,-1,0
       0      .1       0  307.45    .045       0  325.36      .1       0
     420     .06       0     550      .1       0
Bank Sta=307.45,325.36
XS Rating Curve= 0 ,0
Exp/Cntr(USF)=0,0
Exp/Cntr=0.3,0.1

Type RM Length L Ch R = 1 ,607     ,208.6,207.6,204.5
XS GIS Cut Line= 2
1679697.83820544385236.0513303971679258.50188814385595.673016923
#Sta/Elev= 30
       0 1017.56    28.1  999.74      45  993.42    64.3  981.96    81.2  974.02
    90.1   967.4   103.9  964.61   114.4  958.99   131.5  953.46   160.7  935.01
   180.6  927.41   198.7  925.52     283   923.2   360.7  922.98  367.47 921.306
   374.4     920  383.32921.3062   413.7  924.11   423.9  930.86   442.2   949.3
   449.1  950.63   462.3  950.17   467.5  951.97   470.6   956.2   476.3  966.86
   480.7  971.71   499.7  983.99   521.6  995.57   541.6  1009.2   567.8 1021.88
#Mann= 7 ,-1,0
       0      .1       0     310     .05       0     340      .1       0
  367.47    .045       0  383.32      .1       0     440     .06       0
  567.75      .1       0
Bank Sta=367.47,383.32
XS Rating Curve= 0 ,0
Exp/Cntr(USF)=0,0
Exp/Cntr=0.3,0.1

Type RM Length L Ch R = 1 ,399     ,166.4,176.8,177.4
XS GIS Cut Line= 2
1679483.29405305385044.2402633281679133.96129017385511.899161644
#Sta/Elev= 30
       0  997.54    45.3  977.56    65.4  965.92    96.8  953.38   105.4  948.44
   120.2  937.65   140.2  926.72     159  923.57   190.1  921.54     280  920.62
   374.8  921.65  396.42918.7306   404.8  917.93  412.21918.7308   428.3  922.81
   433.1  925.68   442.6  933.43   445.5  935.06   449.7  935.94   459.8  935.94
   464.7  937.55   474.7     948   482.6  954.24   499.8  962.28   509.6  969.83
     520  973.17   534.6  981.09   560.1  991.21   568.4  996.34   583.7 1008.39
#Mann= 6 ,-1,0
       0      .1       0     210     .05       0     370     .06       0
  396.42    .045       0  412.21     .06       0     510      .1       0
Bank Sta=396.42,412.21
XS Rating Curve= 0 ,0
Exp/Cntr(USF)=0,0
Exp/Cntr=0.3,0.1

Type RM Length L Ch R = 1 ,222     ,55.6,51.2,50.1
XS GIS Cut Line= 4
1679489.76864334385024.9942145611679292.19714333385065.999620223
1679054.86282571385348.0671076591679067.02008588385500.741533884
#Sta/Elev= 30
       0 1005.67    50.7  983.43    82.2  967.04   109.3  956.82   124.2  949.47
   140.6  939.38   156.6  936.79   173.3  932.02   193.7  928.39   209.3  927.55
   220.8  925.48   278.3     922   388.1  919.57   456.6  919.85   473.3  920.76
     479  919.93   487.4  917.03   498.9  917.47   518.7  916.66  529.75  917.48
   534.4  919.95   539.7  924.18   544.9  925.99   570.9  926.85   583.2  937.25
   590.9   945.4     599  951.28     611  956.74   651.1  981.07   723.6 1017.96
#Mann= 8 ,-1,0
       0      .1       0  251.78     .06       0  401.78     .05       0
  441.78     .07       0   498.9    .045       0  529.75     .07       0
  561.78     .06       0  670.41      .1       0
#XS Ineff= 2 , 0
          473.31  930.69
Permanent Ineff=
       F       F
Bank Sta=498.9,529.75
XS Rating Curve= 0 ,0
Exp/Cntr(USF)=0,0
Exp/Cntr=0.3,0.1