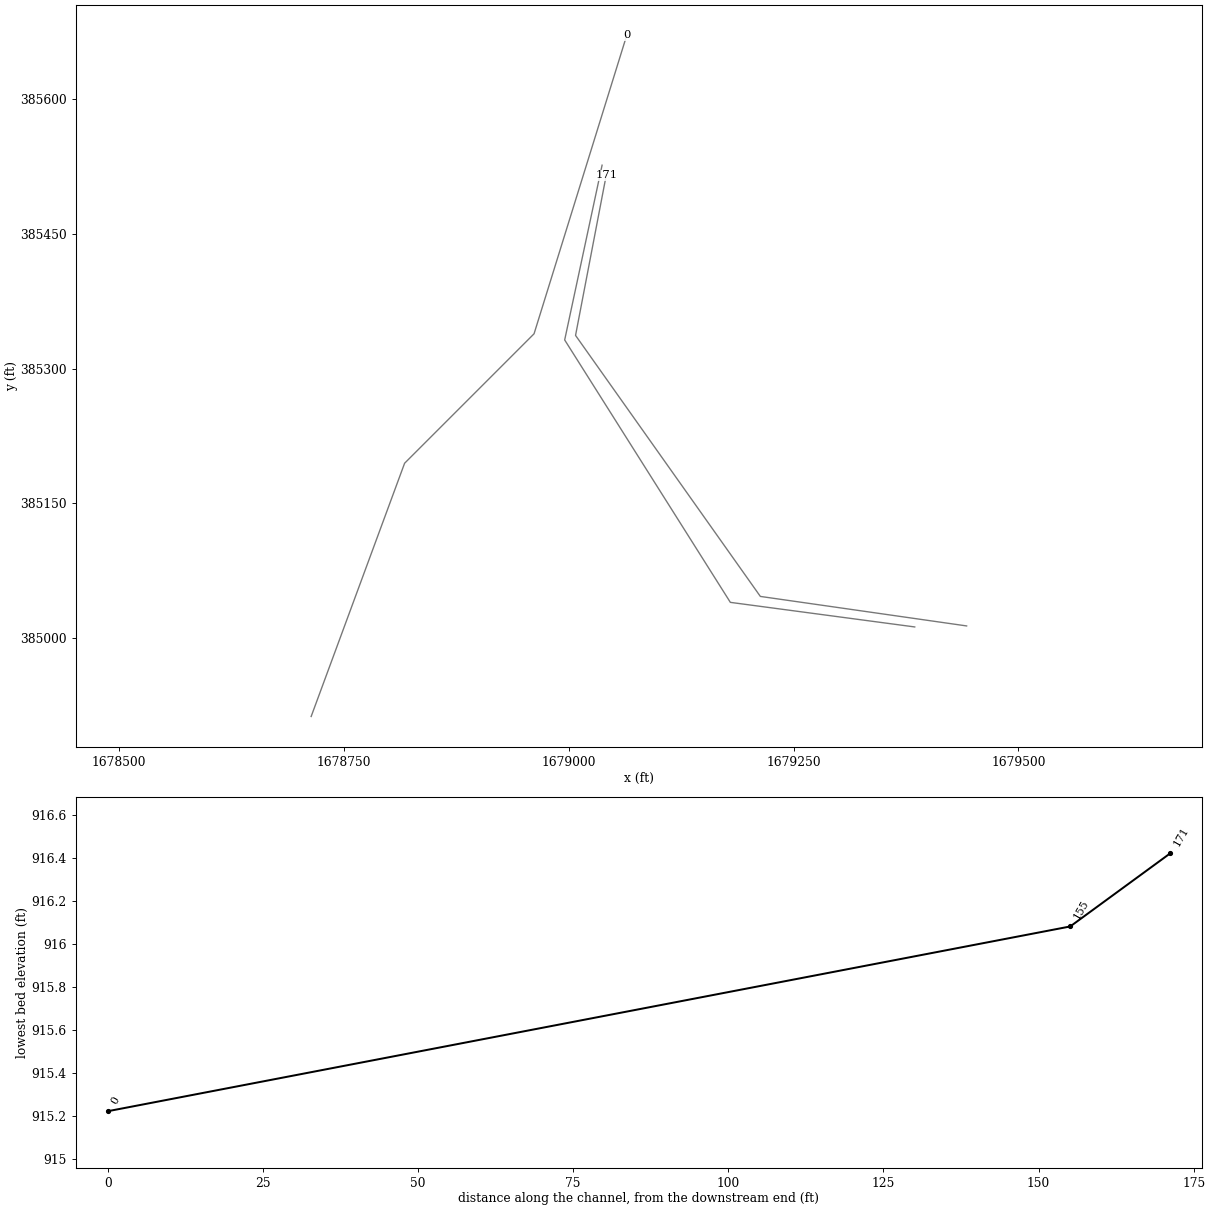
HEC-RAS study WILEYFK.prj: WILEYFK

--- WILEYFK.g01 (geometry) --- (continued)

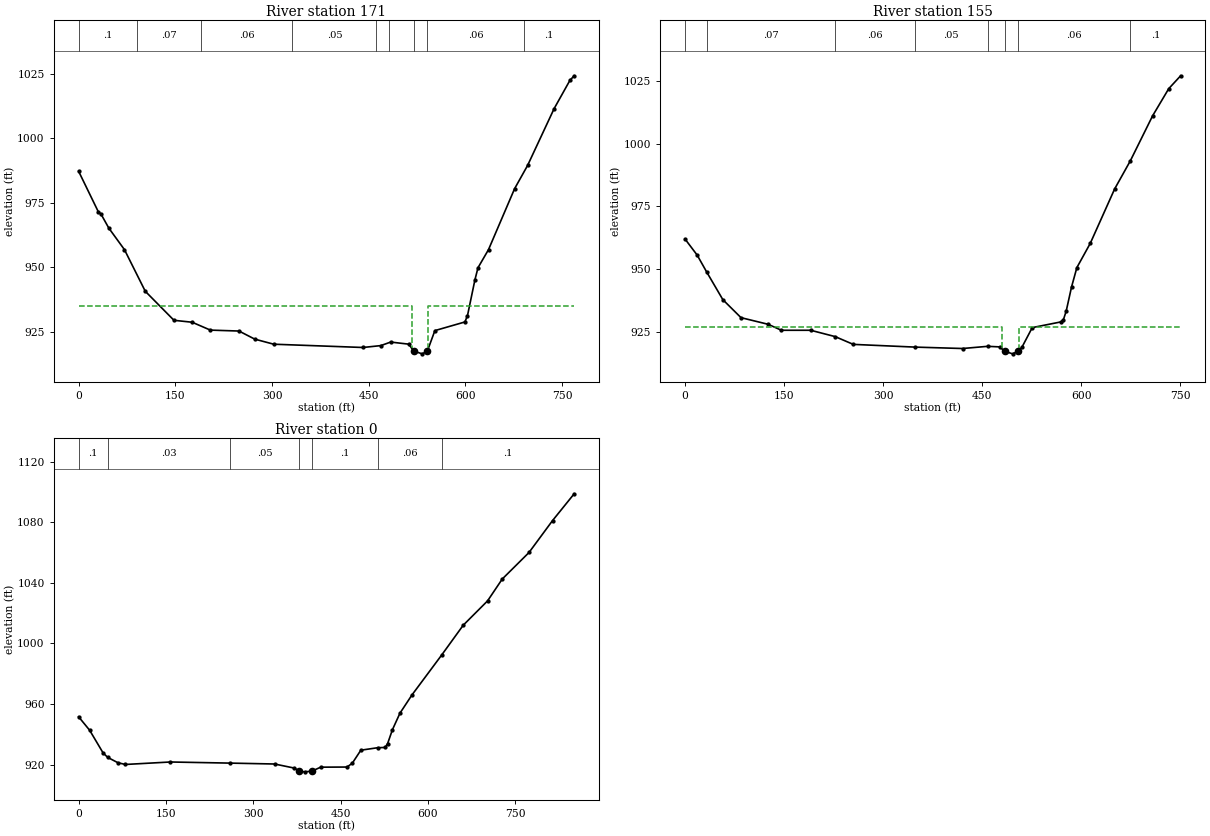
Type RM Length L Ch R = 1 ,171     ,16.6,16.1,15.4
BEGIN DESCRIPTION:
IFAs helps resolve drawdown
END DESCRIPTION:
XS GIS Cut Line= 4
1679442.48224021385013.7768934951679213.08958423385046.599716195
1679007.57642258385336.849786593 1679041.7237789385515.080270517
#Sta/Elev= 30
       0  987.12    30.7  971.36    34.7  970.55    46.8  965.13    71.1  956.77
   103.4  940.65   147.9  929.41   176.1  928.66   204.4  925.61   248.8  925.25
   273.3  922.11   302.7  920.15   441.1  918.88   468.8  919.61   484.1  920.98
   512.2  920.17   519.8917.4842   533.1  916.42  541.02  917.48   552.7  925.42
   599.3  928.77   603.3  931.25   614.9  945.17   619.6  949.78   635.9  956.79
   676.4   980.4   696.5  989.37   737.7  1011.4   762.2 1022.35   768.8 1024.12
#Mann= 9 ,-1,0
       0      .1       0      90     .07       0     190     .06       0
  331.78     .05       0  461.78     .07       0  481.78     .06       0
   519.8    .045       0  541.02     .06       0  690.41      .1       0
#XS Ineff= 2 , 0
          516.62  935.04  542.37          935.11
Permanent Ineff=
       F       F
Bank Sta=519.8,541.02
XS Rating Curve= 0 ,0
Exp/Cntr(USF)=0,0
Exp/Cntr=0.3,0.1

Type RM Length L Ch R = 1 ,155     ,171.4,155.1,143.3
BEGIN DESCRIPTION:
IFAs helps resolve drawdown
END DESCRIPTION:
XS GIS Cut Line= 4
1679384.76973899     385012.65751679179.72695047385039.996538469
1678995.48560426385331.8110577821679037.08848889385526.155961683
#Sta/Elev= 30
       0  961.94    18.3  955.54    32.5  948.88    57.2  937.73    84.7  930.54
   125.8  927.89   145.9   925.5   190.3   925.5   227.3  922.97   254.8  919.86
   348.5  918.77   420.4  918.21   458.2  919.08   476.6  918.86  483.89917.1397
   496.1  916.08   504.6917.1395   510.3  918.73   525.9  926.56   569.1  928.83
   573.2   929.8   577.3  933.12   585.4  942.78   593.5  950.55   613.8  960.25
   650.8  982.03   674.4  993.18   708.2  1011.2   732.7 1022.08   750.7 1027.22
#Mann= 8 ,-1,0
       0      .1       0    32.5     .07       0   227.3     .06       0
   348.5     .05       0   458.2     .06       0  483.89    .045       0
   504.6     .06       0   674.4      .1       0
#XS Ineff= 2 , 0
          480.58  926.76  506.03          926.83
Permanent Ineff=
       F       F
Bank Sta=483.89,504.6
XS Rating Curve= 0 ,0
Exp/Cntr(USF)=0,0
Exp/Cntr=0.3,0.1

Type RM Length L Ch R = 1 ,0       ,196.4,203.6,205.8
XS GIS Cut Line= 4
1678713.56641098384913.0828725371678817.47807282385194.701507787
 1678961.4391846385338.6599272721679064.52874707385670.669212739
#Sta/Elev= 30
       0  951.54    18.9  942.69      42  927.72      50924.7422    67.6  921.22
    80.4  920.09   157.6  921.72     260 920.985   336.7  920.39   370.7  917.69
  379.41  915.65   388.2  915.22  400.57  915.65   415.9   918.3   461.2  918.39
   470.2  920.93   484.9  929.51  513.77931.1364   526.7  931.32   530.9  933.91
   539.2  943.08   552.1  953.95   572.7  965.97  623.77992.3373   660.8 1012.01
   702.6 1028.07   727.9 1042.52   773.8    1060   814.2 1081.05   851.4 1098.76
#Mann= 7 ,-1,0
       0      .1       0      50     .03       0     260     .05       0
  379.41    .045       0  400.57      .1       0  513.77     .06       0
  623.77      .1       0
Bank Sta=379.41,400.57
XS Rating Curve= 0 ,0
Exp/Cntr=0.3,0.1
LCMann Table=0

Chan Stop Cuts=-1
Use User Specified Reach Order=0
Composite Channel Slope=5